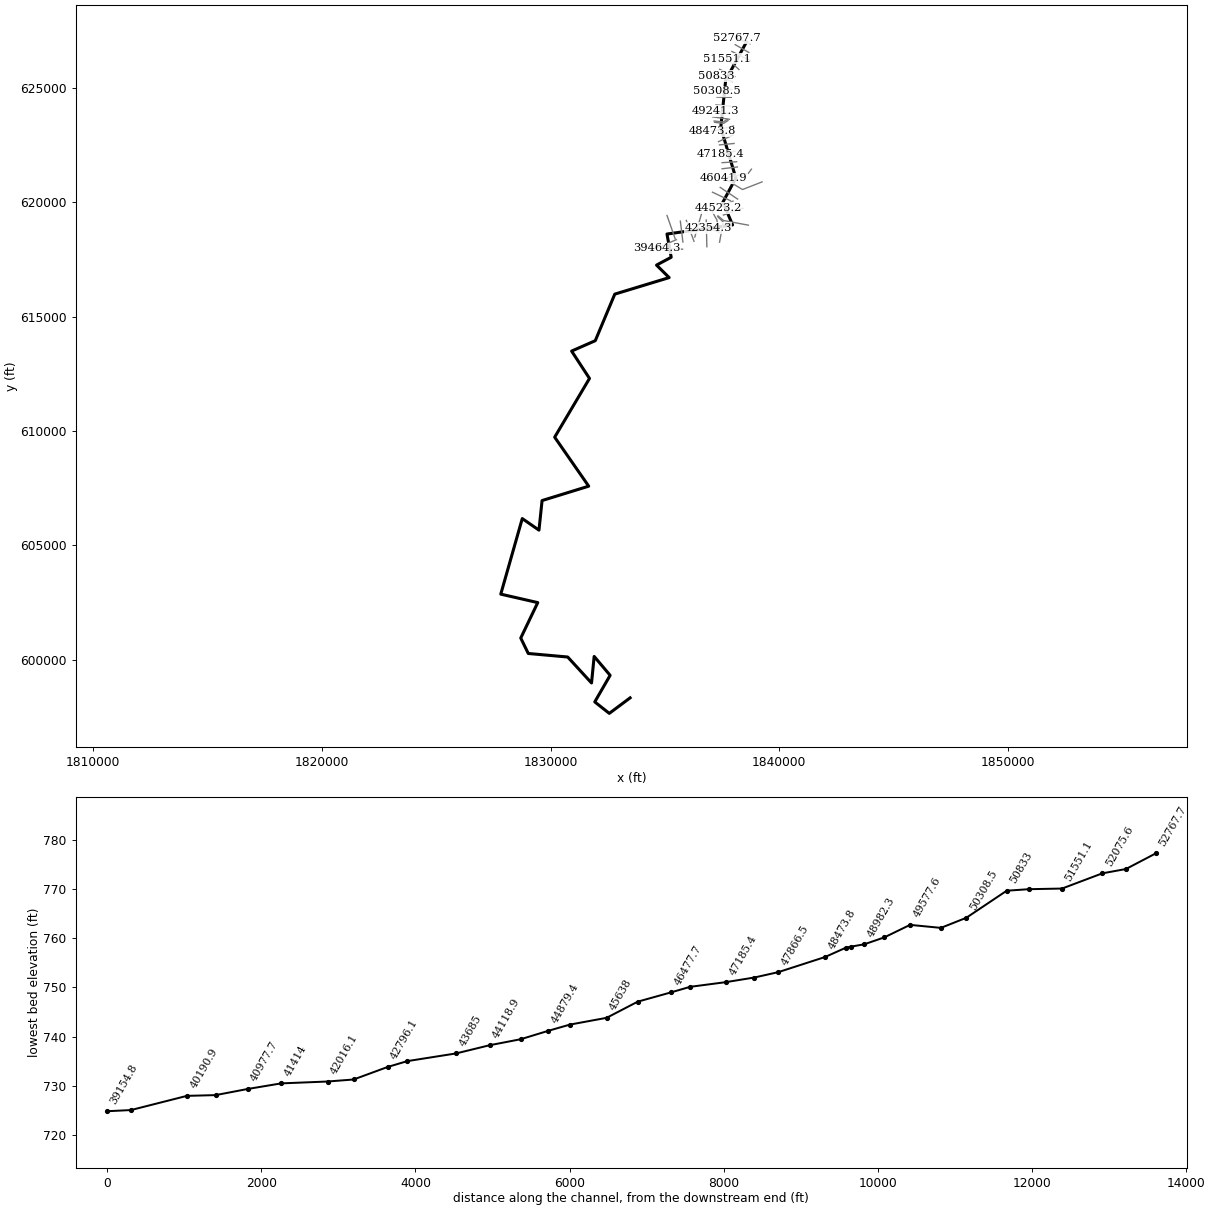
--- FlatFork.prj (project) ---

Proj Title=FlatFork
Current Plan=p01
Default Exp/Contr=0,0
English Units
Geom File=g01
Flow File=f01
Plan File=p01
BEGIN DESCRIPTION:
AMEC Environment & Infrastructure, 2013
Projection: NAD 1983 State Plane West Virginia South FIPS 4702 (US Feet)
Vertical Datum: NAVD 1988
END DESCRIPTION:
DSS Export Rating Curves= 0
DSS Export Rating Curve Sorted= 0
DSS Export Volume Flow Curves= 0
DXF OffsetX= 0
DXF OffsetY= 0
DXF ScaleX= 0
DXF ScaleY= 0

--- FlatFork.p01 (plan) ---

Plan Title=Floodplain
Program Version=4.00
Geom File=g01
Flow File=f01
K Sum by GR=0
Std Step Tol=0.01
Critical Tol=0.01
Num of Std Step Trials=20
Max Error Tol=0.3
Flow Tol Ratio=0.001
Split Flow NTrial=30
Split Flow Tol=0.02
Split Flow Ratio=0.02
Log Output Level=0
Friction Slope Method=1
Unsteady Friction Slope Method=2
Unsteady Bridges Friction Slope Method=1
Global Log Level=0
CheckData=False
Run HTab=0
Run UNet=0
Run PostProcess=0
UNET Theta=0
UNET Theta Warmup=0
UNET ZTol=0
UNET ZSATol=0
UNET MxIter=0
UNET MaxInSteps=0
UNET DtIC=0
UNET DtMin=0
UNET MaxCRTS=0
UNET WFStab=0
UNET SFStab=0
UNET WFX=0
UNET SFX=0
UNET DSS MLevel=0
UNET DZMax Abort=0
UNET Convert EG Bridges=0
UNET Use Existing IB Tables=0
UNET Froude Limit=0
UNET Froude Power=0
Write IC File=0
Echo Input=False
Echo Output=False
Write Detailed=0

--- FlatFork.f01 (steady flow) ---

Flow Title=NFF Regression Equation
Program Version=4.00
Number of Profiles=1
Profile Names=P100yr
River Rch & RM=FlatFork,Main      ,52767.7
1049.564
River Rch & RM=FlatFork,Main      ,49978.4
1149.540
River Rch & RM=FlatFork,Main      ,45638
1265.742
River Rch & RM=FlatFork,Main      ,45162.2
1848.818
River Rch & RM=FlatFork,Main      ,43051.9
2029.534
River Rch & RM=FlatFork,Main      ,40190.9
2142.521
River Rch & RM=FlatFork,Main      ,32120.5
2341.615
River Rch & RM=FlatFork,Main      ,31282
3613.935
River Rch & RM=FlatFork,Main      ,29052.5
3805.988
River Rch & RM=FlatFork,Main      ,15631.3
4129.889
River Rch & RM=FlatFork,Main      ,15166.2
4771.640
River Rch & RM=FlatFork,Main      ,504.9
4975.454
River Rch & RM=FlatFork,Main      ,123.1
4976.756
Boundary for River Rch & Prof#=FlatFork,Main      ,1
Up Type=0
Dn Type=3
Dn Slope=0.001731

--- FlatFork.g01 (geometry) ---

Geom Title=USGS 3m DEM
Program Version=4.10

River Reach=FlatFork        ,Main
Reach XY= 30
     1838560.493      627005.709     1837652.286       625336.67
      1837438.79      623271.702     1838097.249      621061.837
     1837533.217      620007.619     1837954.127      619010.396
     1835086.838      618612.526     1835270.988      617596.561
     1834629.773       617253.57     1835182.466       616707.36
     1832804.953      615984.754     1831952.347      613949.285
     1830917.296      613494.208     1831698.827      612297.892
     1830176.657      609729.652     1831664.412      607587.724
      1829625.56      606958.925      1829490.17      605665.076
      1828759.89       606171.27     1827819.623      602867.164
     1829436.507      602497.337     1828693.286      600948.164
     1829021.558      600272.607     1830746.104      600118.134
     1831788.181       598982.39     1831902.742      600144.246
     1832600.938      599317.615      1831929.47      598155.444
     1832564.554      597653.859     1833474.809      598332.732

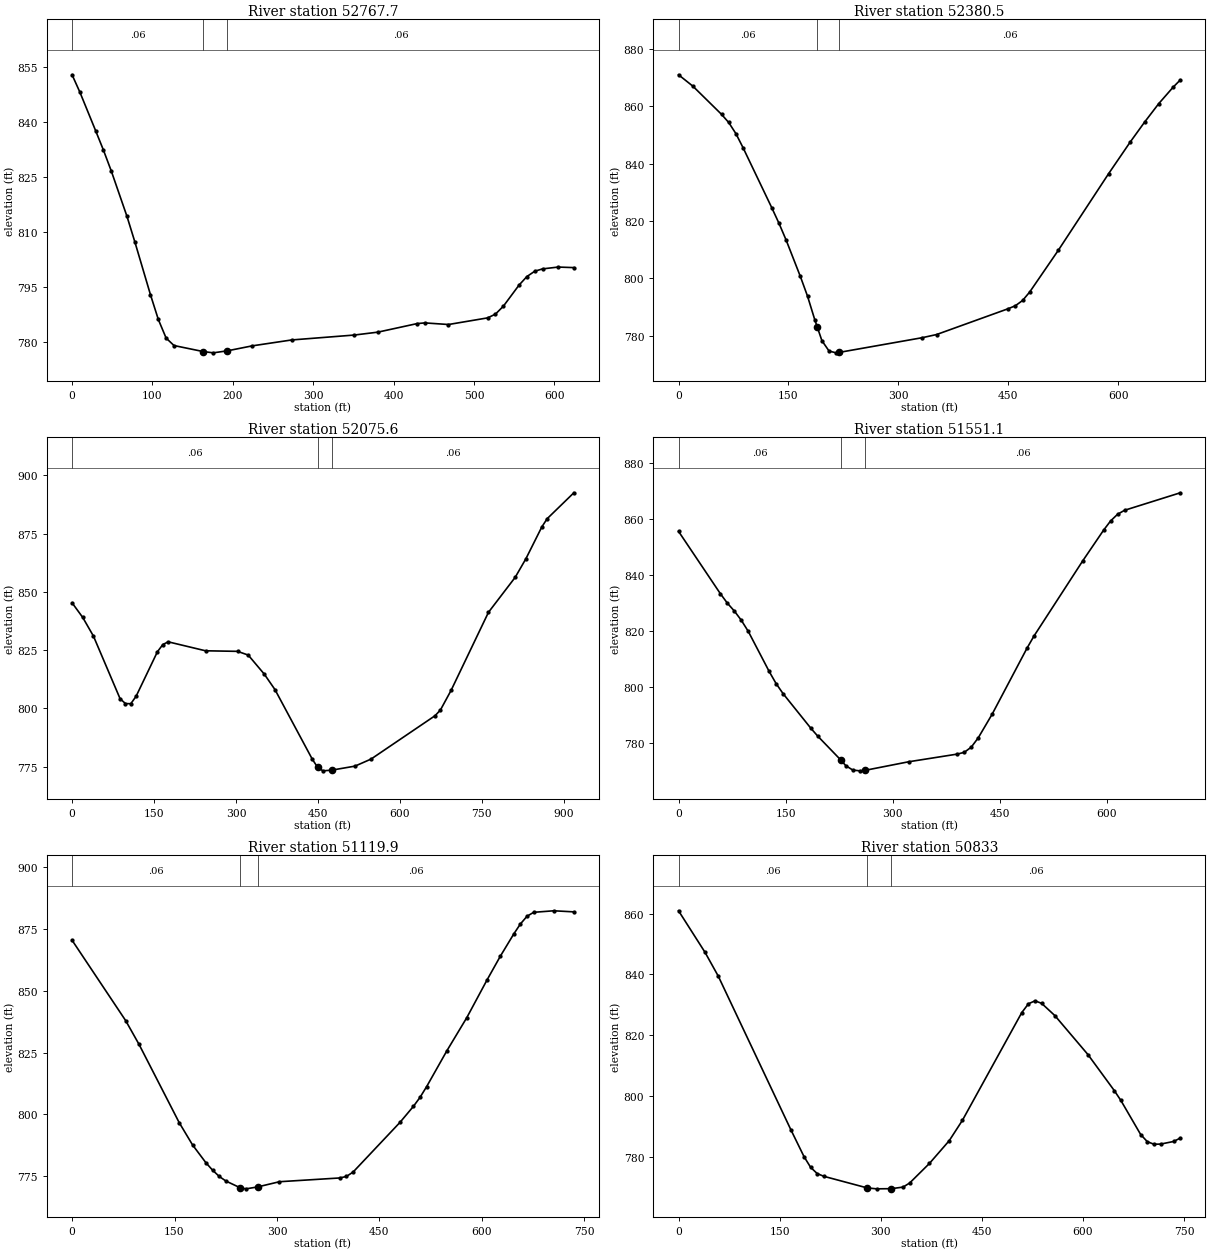
Type RM Length L Ch R = 1 ,52767.7 ,389.4,387,384.6
XS GIS Cut Line= 2
      1838723.53      626930.113     1838146.622       627168.57
#Sta/Elev= 30
       0  852.97     9.8  848.19    29.3  837.73      39  832.45    48.8  826.73
    68.3  814.38      78  807.49    97.5  793.04   107.3  786.27     117   781.2
   126.8  779.17   162.8777.5423   175.6  777.18   193.2777.7318   224.3  779.09
   273.1  780.69   351.1  782.03   380.4  782.82   429.2  785.15   438.9  785.34
   468.2   784.9     517  786.71   526.7  787.74   536.5  789.89     556  795.64
   565.7  797.96   575.5  799.42   585.2  800.06   604.7  800.56   624.2  800.41
#Mann= 3 , 0 , 0
       0     .06       0   162.8    .045       0   193.2     .06       0
Bank Sta=162.8,193.2
XS Rating Curve= 0 ,0
Exp/Cntr=0.3,0.1

Type RM Length L Ch R = 1 ,52380.5 ,303.8,305.1,306.5
XS GIS Cut Line= 2
     1838663.834      626552.034     1838069.509      626892.381
#Sta/Elev= 30
       0  870.97    19.6  866.99    58.7  857.17    68.5  854.33    78.3  850.45
    88.1  845.52   127.2  824.64     137  819.24   146.8  813.37   166.3  800.63
   176.1  793.74   185.9   785.6   189.4 782.975   195.7  778.25   205.5  774.62
   215.2  774.01     219774.1535   332.6  779.29   352.2  780.39   450.1  789.41
   459.8  790.44   469.6  792.27   479.4  795.25   518.6  809.86     587  836.48
   616.4  847.48     636  854.42   655.5  860.93   675.1  866.65   684.9  869.18
#Mann= 3 , 0 , 0
       0     .06       0   189.4    .045       0     219     .06       0
Bank Sta=189.4,219
XS Rating Curve= 0 ,0
Exp/Cntr=0.3,0.1

Type RM Length L Ch R = 1 ,52075.6 ,530.5,523.8,516.8
XS GIS Cut Line= 2
     1838747.845      626188.327      1837924.24      626594.813
#Sta/Elev= 30
       0  845.29    19.5  839.02    39.1     831    87.9   804.1    97.7  802.03
   107.5  801.96   117.2  805.16   156.3  824.31   166.1  827.36   175.9  828.54
   244.3  824.69   302.9  824.45   322.4  822.85   351.8  814.67   371.3  808.05
   439.7  778.12   449.5  774.63   459.2  773.14   475.1773.4363   517.8  775.16
   547.2  778.19   664.4  796.82   674.2  799.27   693.7  807.69   762.1  841.21
     811  856.23   830.5  864.16   859.8  877.89   869.6  881.43   918.4  892.54
#Mann= 3 , 0 , 0
       0     .06       0   449.5    .045       0   475.1     .06       0
Bank Sta=449.5,475.1
XS Rating Curve= 0 ,0
Exp/Cntr=0.3,0.1

Type RM Length L Ch R = 1 ,51551.1 ,424.5,431.2,438.3
XS GIS Cut Line= 2
     1838231.224       625807.44     1837711.208      626280.763
#Sta/Elev= 30
       0   855.6    58.6  833.34    68.4  829.96    78.1  827.17    87.9  823.87
    97.7  819.88     127  805.56   136.7  801.23   146.5  797.63   185.6  785.21
   195.3  782.39     227774.0194   234.4  771.89   244.2  770.33   253.9  770.05
   261.6770.2385   322.3  773.28   390.6  776.03   400.4  776.66   410.2  778.51
     420  781.84   439.5  790.29   488.3  813.85   498.1   818.2   566.4  845.05
   595.7  856.04   605.5  859.32   615.3  861.71     625  863.12   703.2  869.38
#Mann= 3 , 0 , 0
       0     .06       0     227    .045       0   261.6     .06       0
Bank Sta=227,261.6
XS Rating Curve= 0 ,0
Exp/Cntr=0.3,0.1

Type RM Length L Ch R = 1 ,51119.9 ,280.4,286.7,289.5
XS GIS Cut Line= 2
     1838052.946      625499.067      1837388.66      625813.259
#Sta/Elev= 30
       0  870.48    78.4  838.01      98  828.39   156.8  796.74   176.4   787.7
     196  780.48   205.8  777.46   215.6  774.92   225.4  773.06   246.2  770.35
   254.8  769.92   271.6770.6883   303.7   772.8   391.9  774.32   401.7  774.93
   411.5   776.7   480.1  796.78   499.7  803.23   509.5  806.91   519.3  811.31
   548.7   825.7   578.1  839.21   607.5  854.34   627.1  864.01   646.7  872.97
   656.5  877.06   666.3  880.21     676  881.78   705.4   882.4   734.8  881.96
#Mann= 3 , 0 , 0
       0     .06       0   246.2    .045       0   271.6     .06       0
Bank Sta=246.2,271.6
XS Rating Curve= 0 ,0
Exp/Cntr=0.3,0.1

Type RM Length L Ch R = 1 ,50833   ,517.2,524.2,534.6
XS GIS Cut Line= 2
     1837949.481       625277.13     1837246.931      625522.771
#Sta/Elev= 30
       0  860.92    39.2  847.31    58.8  839.51   166.5  789.07   186.1   780.2
   195.9  776.68   205.6  774.64   215.4  773.73   279.7769.9218   293.8  769.61
   315.7769.6664     333  770.18   342.8  771.52   372.1  777.94   401.5  785.42
   421.1  792.12   509.2  827.51     519  830.38   528.8  831.35   538.6  830.52
   558.2   826.5   607.2  813.72   646.3  801.89   656.1  798.64   685.5  787.44
   695.3  785.11   705.1  784.26   714.9   784.3   734.5  785.17   744.3   786.3
#Mann= 3 , 0 , 0
       0     .06       0   279.7    .045       0   315.7     .06       0
Bank Sta=279.7,315.7
XS Rating Curve= 0 ,0
Exp/Cntr=0.3,0.1

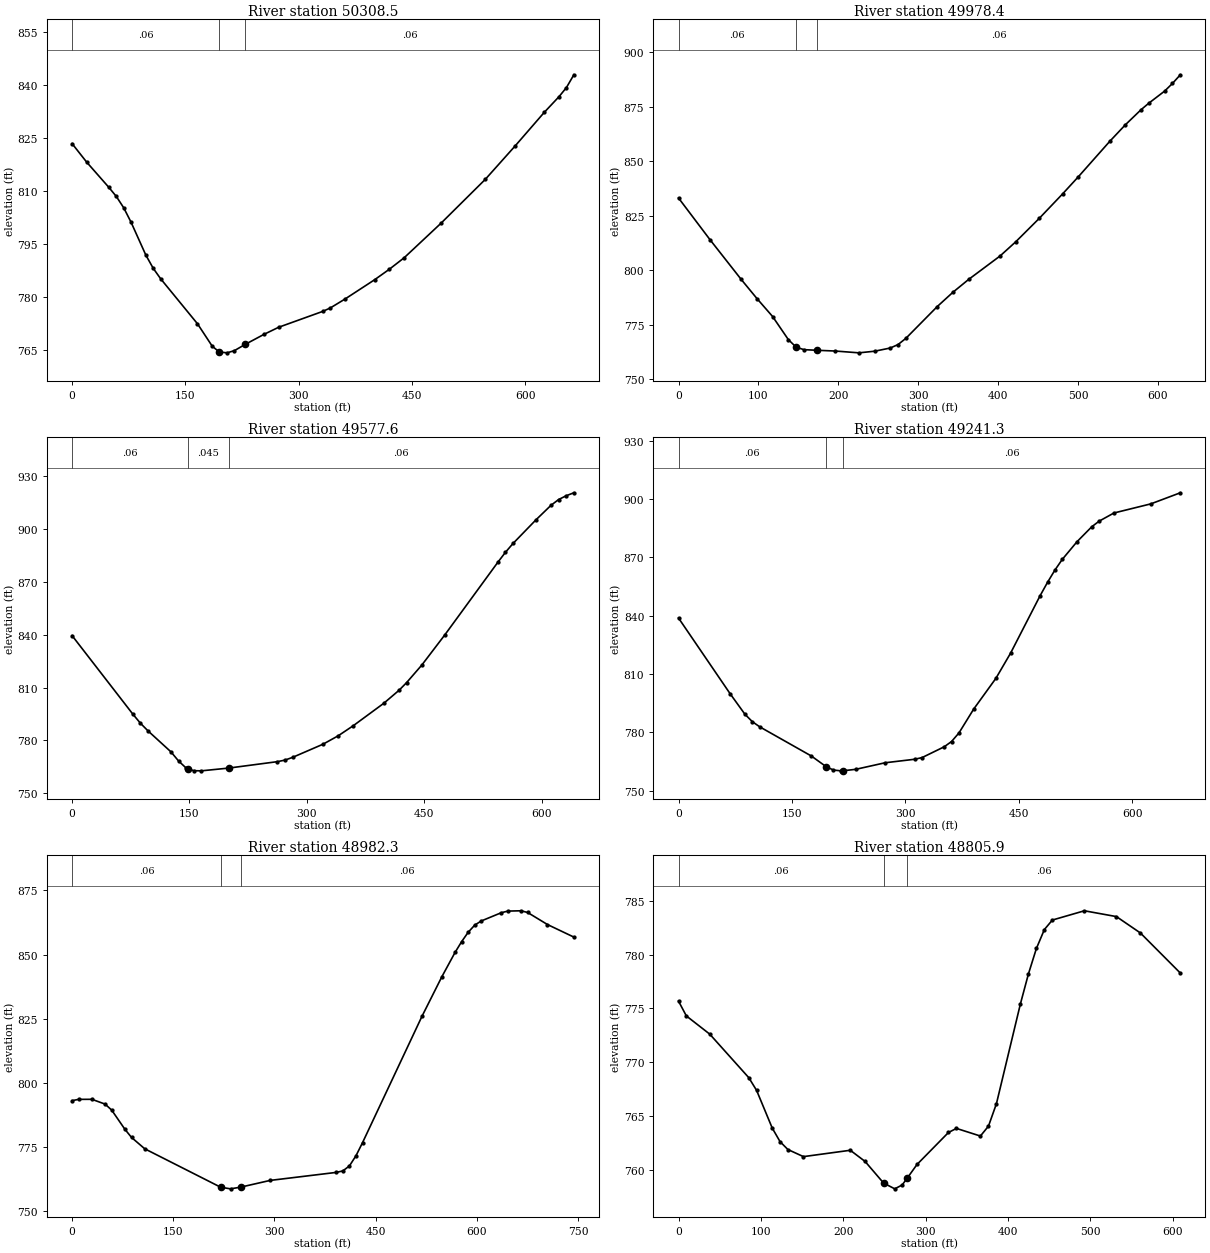
Type RM Length L Ch R = 1 ,50308.5 ,332.7,329.7,326.8
XS GIS Cut Line= 2
     1837930.825       624937.91     1837271.537      624858.255
#Sta/Elev= 30
       0  823.35    19.5  818.06    48.8  810.93    58.6  808.38    68.4  805.16
    78.1  801.08    97.7  791.76   107.4  788.05   117.2   785.1     166  772.34
   185.6  765.97   194.9764.3688   205.1  764.12   214.8  764.74   229.2766.5167
   253.9  769.34   273.4  771.36     332  775.87   341.8  776.83   361.3  779.36
   400.4  784.81   419.9  787.78   439.5  791.03   488.3  800.81   546.9  813.23
     586  822.59     625  832.21   644.6  836.67   654.3  839.22   664.1  842.83
#Mann= 3 , 0 , 0
       0     .06       0   194.9    .045       0   229.2     .06       0
Bank Sta=194.9,229.2
XS Rating Curve= 0 ,0
Exp/Cntr=0.3,0.1

Type RM Length L Ch R = 1 ,49978.4 ,402.1,400,397.9
XS GIS Cut Line= 2
     1837901.146      624589.184     1837273.301      624598.274
#Sta/Elev= 30
       0  833.11    39.2  814.07    78.5  795.72    98.1  786.99   117.7  778.74
   137.4  768.15   147.2  764.66     157  763.53   172.7763.2518   196.2   762.9
   225.7  762.07   245.3  762.81   264.9  764.28   274.7  765.87   284.5  768.73
   323.8  783.33   343.4  789.88     363  795.75   402.3   806.5   421.9     813
   451.3  823.74   480.7  835.04   500.4   842.9   539.6  859.11   559.2  866.73
   578.9  873.67   588.7  876.68   608.3  882.18   618.1  885.69   627.9  889.65
#Mann= 3 , 0 , 0
       0     .06       0   147.2    .045       0   172.7     .06       0
Bank Sta=147.2,172.7
XS Rating Curve= 0 ,0
Exp/Cntr=0.3,0.1

Type RM Length L Ch R = 1 ,49577.6 ,341.2,336,331.5
XS GIS Cut Line= 2
     1837868.071      624200.545     1837229.744      624259.187
#Sta/Elev= 30
       0  839.47    77.7  794.84    87.4  789.68    97.1  785.33   126.3  773.47
     136   768.3   145.7  764.27   148.5763.8342   155.4  762.76   165.1  762.68
     200764.2413   262.2  767.89     272  768.78   281.7  770.33   320.5  777.79
   339.9  782.56   359.4  788.36   398.2  801.04   417.6  808.39   427.3  812.76
   446.8  822.76   475.9  839.72   543.9  881.12   553.6  886.77   563.3  891.79
   592.4  905.12   611.9   913.5   621.6  916.75   631.3   918.9     641  920.57
#Mann= 3 , 0 , 0
       0     .06       0   148.5    .045       0     200     .06       0
Bank Sta=148.5,200
XS Rating Curve= 0 ,0
Exp/Cntr=0.3,0.1

Type RM Length L Ch R = 1 ,49241.3 ,255.5,258.8,261.5
XS GIS Cut Line= 2
     1837840.227      623873.385     1837187.074      623990.265
#Sta/Elev= 30
       0  838.79    68.3  799.78    87.8  789.26    97.6  785.44   107.3   782.8
   175.6  767.77   195.2  762.27   204.9  760.53   214.7  760.13   218.1760.2036
   234.2   760.9   273.2  764.29   312.2  766.09     322  766.95   351.3  772.51
     361  775.23   370.8  779.64   390.3  791.94   419.6  807.73   439.1  820.75
   478.1   850.3   487.9  857.17   497.6  863.44   507.4  868.99   526.9  878.09
   546.4  885.79   556.2  888.68   575.7  892.87   624.5  897.57   663.5  903.28
#Mann= 3 , 0 , 0
       0     .06       0   195.2    .045       0   218.1     .06       0
Bank Sta=195.2,218.1
XS Rating Curve= 0 ,0
Exp/Cntr=0.3,0.1

Type RM Length L Ch R = 1 ,48982.3 ,175.4,176.4,177.3
XS GIS Cut Line= 2
     1837819.501       623629.85      1837083.15       623735.21
#Sta/Elev= 30
       0  793.09     9.8  793.59    29.4  793.61    48.9  791.75    58.7  789.42
    78.3  781.94    88.1  778.77   107.7  774.34   220.4759.3516   234.9  758.74
   249.7 759.388   293.6  762.02   391.5  765.14   401.3  765.71   411.1  767.66
   420.9  771.65   430.6  776.75   518.7  825.96   548.1  841.33   567.7  850.82
   577.5  855.04   587.2  858.69     597  861.49   606.8   863.1   636.2  866.28
     646  866.92   665.6  867.04   675.3  866.37   704.7  861.68   743.8  856.79
#Mann= 3 , 0 , 0
       0     .06       0   220.4    .045       0   249.7     .06       0
Bank Sta=220.4,249.7
XS Rating Curve= 0 ,0
Exp/Cntr=0.3,0.1

Type RM Length L Ch R = 1 ,48805.9 ,60.5,60.6,60.7
XS GIS Cut Line= 4
     1837722.638       623623.13     1837545.832      623512.402
     1837456.292      623521.828     1837147.046       623552.82
#Sta/Elev= 30
       0  775.67     9.5   774.3    37.9  772.61    85.3  768.57    94.8  767.39
   113.8  763.89   123.3  762.63   132.8   761.9   151.7  761.24   208.6  761.83
   226.6  760.79     249758.7875   262.6  758.25   271.6  758.61   277.9 759.261
   289.6  760.51   327.8  763.48   337.5  763.86   366.6  763.15   376.4  764.07
   386.1  766.16   415.2  775.42   424.9  778.19   434.6  780.56   444.3  782.32
     454   783.2   492.9  784.06   531.8  783.52   560.9     782   609.4  778.28
#Mann= 3 , 0 , 0
       0     .06       0     249    .045       0   277.9     .06       0
Bank Sta=249,277.9
XS Rating Curve= 0 ,0
Exp/Cntr=0.3,0.1

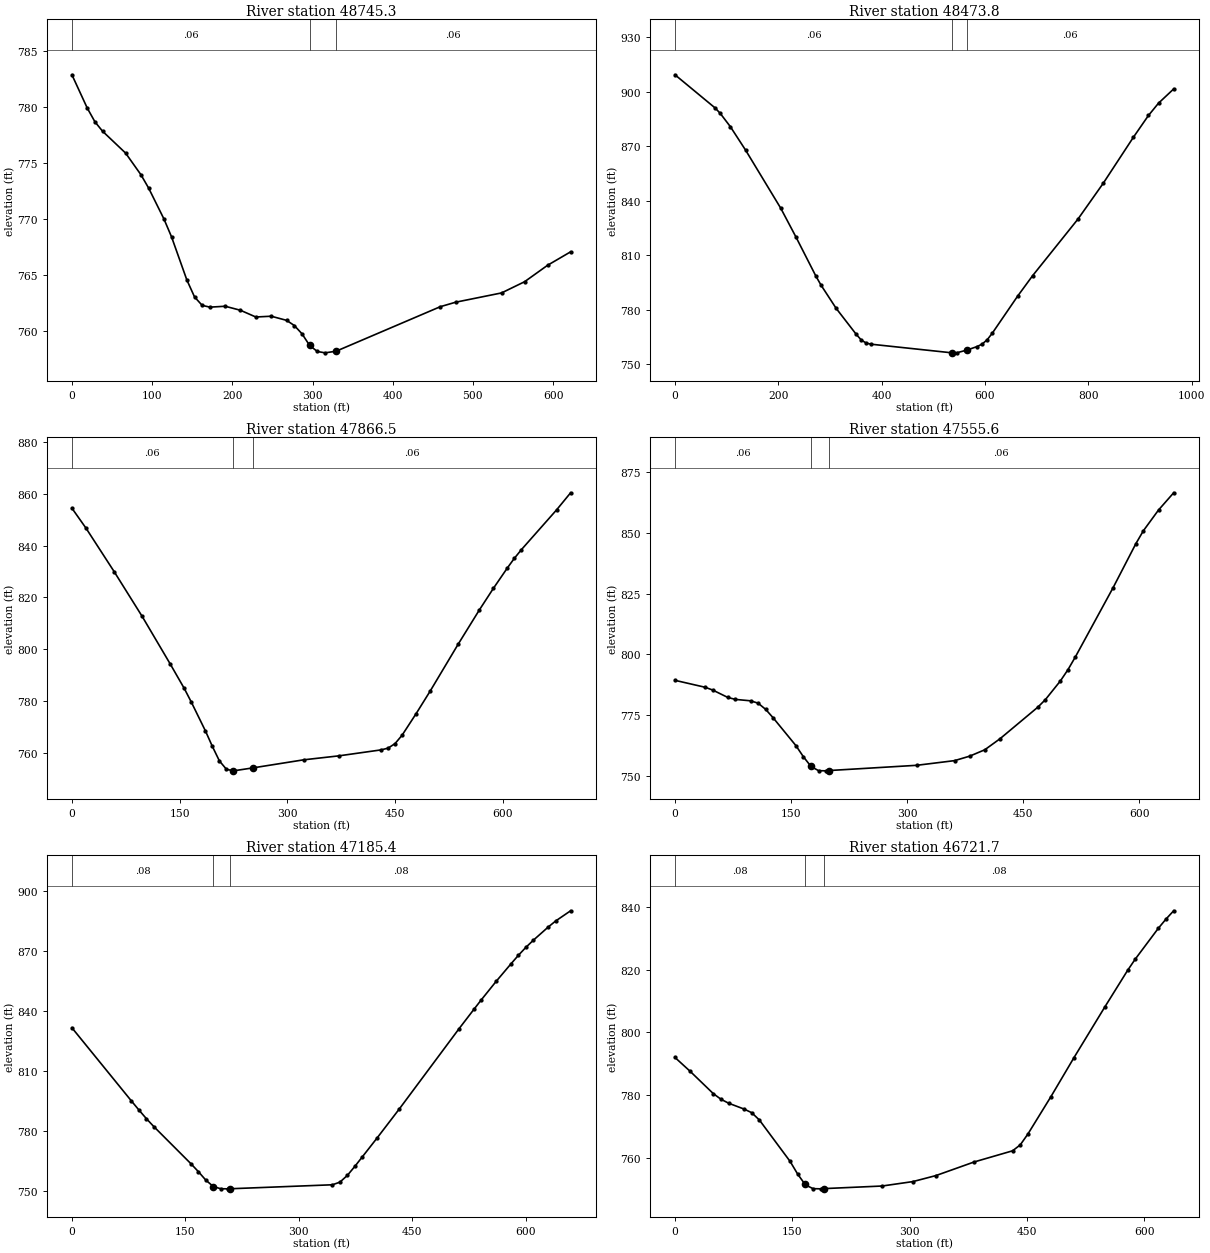
Type RM Length L Ch R = 1 ,48745.3 ,263.7,271.4,279.1
XS GIS Cut Line= 4
     1837754.484      623572.279     1837560.136      623450.565
     1837435.981      623463.634     1837170.373      623496.168
#Sta/Elev= 30
       0  782.89    19.1  779.92    28.7  778.69    38.2  777.85    66.9   775.9
      86  773.97    95.6  772.78   114.7  770.02   124.2  768.42   143.3  764.57
   152.9  763.05   162.4   762.3     172  762.14   191.1  762.22   210.2  761.86
   229.3  761.26   248.5  761.33   267.7  760.96   277.3   760.5   286.9  759.76
   296.4758.7209     306  758.18   315.7  758.06   329.4 758.205   459.3  762.18
   478.4  762.58   535.7  763.41   564.4  764.41   593.1  765.88   621.8  767.08
#Mann= 3 , 0 , 0
       0     .06       0   296.4    .045       0   329.4     .06       0
Bank Sta=296.4,329.4
XS Rating Curve= 0 ,0
Exp/Cntr=0.3,0.1

Type RM Length L Ch R = 1 ,48473.8 ,602.8,606.8,610.5
XS GIS Cut Line= 2
     1837995.838      623333.134      1837059.49      623098.935
#Sta/Elev= 30
       0  909.37      78  891.01    87.7  888.06   107.2  880.77   136.5  867.93
   204.7  835.85     234  820.06     273  798.29   282.7  793.45     312  780.65
     351  766.29   360.7  763.19   370.5  761.48   380.2   760.9   536.2  756.16
   536.6756.1631     546  756.24   564.7757.6543     585  759.64   594.7  761.03
   604.5  763.44   614.2  767.01     663  787.33   692.2  798.68     780  829.88
   828.7  849.52   887.2  874.93   916.4  886.95   935.9  893.74   965.2  901.56
#Mann= 3 , 0 , 0
       0     .06       0   536.6    .045       0   564.7     .06       0
Bank Sta=536.6,564.7
XS Rating Curve= 0 ,0
Exp/Cntr=0.3,0.1

Type RM Length L Ch R = 1 ,47866.5 ,318.6,310.8,303.1
XS GIS Cut Line= 2
     1837971.001      622937.744     1837339.055      622650.567
#Sta/Elev= 30
       0  854.42    19.6  846.71    58.7  829.98    97.8  812.66   136.9  794.28
   156.4  784.86   166.2   779.6   185.8  768.51   195.5  762.51   205.3  756.91
   215.1  753.68   223.6753.1683   224.9  753.09   251.7754.2211   322.6  757.34
   371.5  758.87   430.2  761.17     440  761.84   449.7  763.59   459.5  766.81
     479  775.12   498.6  783.84   537.7     802     567  815.12   586.6  823.48
   606.2  831.41   615.9  835.11   625.7  838.45   674.6  853.77   694.1  860.36
#Mann= 3 , 0 , 0
       0     .06       0   223.6    .045       0   251.7     .06       0
Bank Sta=223.6,251.7
XS Rating Curve= 0 ,0
Exp/Cntr=0.3,0.1

Type RM Length L Ch R = 1 ,47555.6 ,367.4,370.1,372.8
XS GIS Cut Line= 2
      1838021.56      622571.791     1837380.004      622509.365
#Sta/Elev= 30
       0   789.3    39.1  786.43    48.8  785.29    68.4  782.23    78.1  781.44
    97.7  780.86   107.4  779.89   117.2  777.34     127  773.81   156.3   762.4
     166   757.8   175.8  753.82   185.6  752.07   195.3     752   198.6752.1111
   312.5  754.28   361.4  756.21   380.9  758.05   400.4  760.67     420  765.19
   468.8  778.18   478.6  781.28   498.1  789.02   507.9  793.65   517.6  798.99
   566.4  827.54   595.8  845.66   605.5  850.97     625  859.48   644.6  866.59
#Mann= 3 , 0 , 0
       0     .06       0   175.8    .045       0   198.6     .06       0
Bank Sta=175.8,198.6
XS Rating Curve= 0 ,0
Exp/Cntr=0.3,0.1

Type RM Length L Ch R = 1 ,47185.4 ,466.5,463.5,460.6
XS GIS Cut Line= 2
     1838068.073      622235.127      1837423.78      622095.123
#Sta/Elev= 30
       0  831.51    78.7  794.94    88.6  790.43    98.4  786.14   108.2  782.19
   157.4  763.58   167.3   759.6   177.1  755.38     187   752.2   196.8  751.11
     206  751.06   209.6751.1044   344.4  753.09   354.3   754.4   364.1  757.76
     374  762.25   383.8  766.97   403.5  776.48     433  791.04   511.7  830.99
   531.4  840.68   541.2  845.45   560.9   854.7   580.6   863.5   590.4  867.75
   600.3  871.73   610.1  875.25   629.8  881.86   639.6  884.86   659.3  889.94
#Mann= 3 , 0 , 0
       0     .08       0     187    .045       0   209.6     .08       0
Bank Sta=187,209.6
XS Rating Curve= 0 ,0
Exp/Cntr=0.3,0.1

Type RM Length L Ch R = 1 ,46721.7 ,242.8,243.9,245
XS GIS Cut Line= 2
     1838131.991      621772.484     1837495.538       621732.15
#Sta/Elev= 30
       0  791.98    19.6  787.52    49.1  780.43    58.9  778.65    68.7  777.39
    88.3  775.54    98.1  774.38   107.9  772.06   147.2  758.86     157  754.76
     166751.6467   166.8  751.37   176.6  750.17   186.4  750.11   190.9750.1863
   264.9  751.01   304.2  752.42   333.6  754.33   382.6  758.68   431.7  762.23
   441.5  764.12   451.3  767.58   480.8  779.52   510.2  791.92   549.4  807.97
   578.9  819.78   588.7  823.37   618.1  833.16   627.9  836.09   637.7  838.73
#Mann= 3 , 0 , 0
       0     .08       0     166    .045       0   190.9     .08       0
Bank Sta=166,190.9
XS Rating Curve= 0 ,0
Exp/Cntr=0.3,0.1

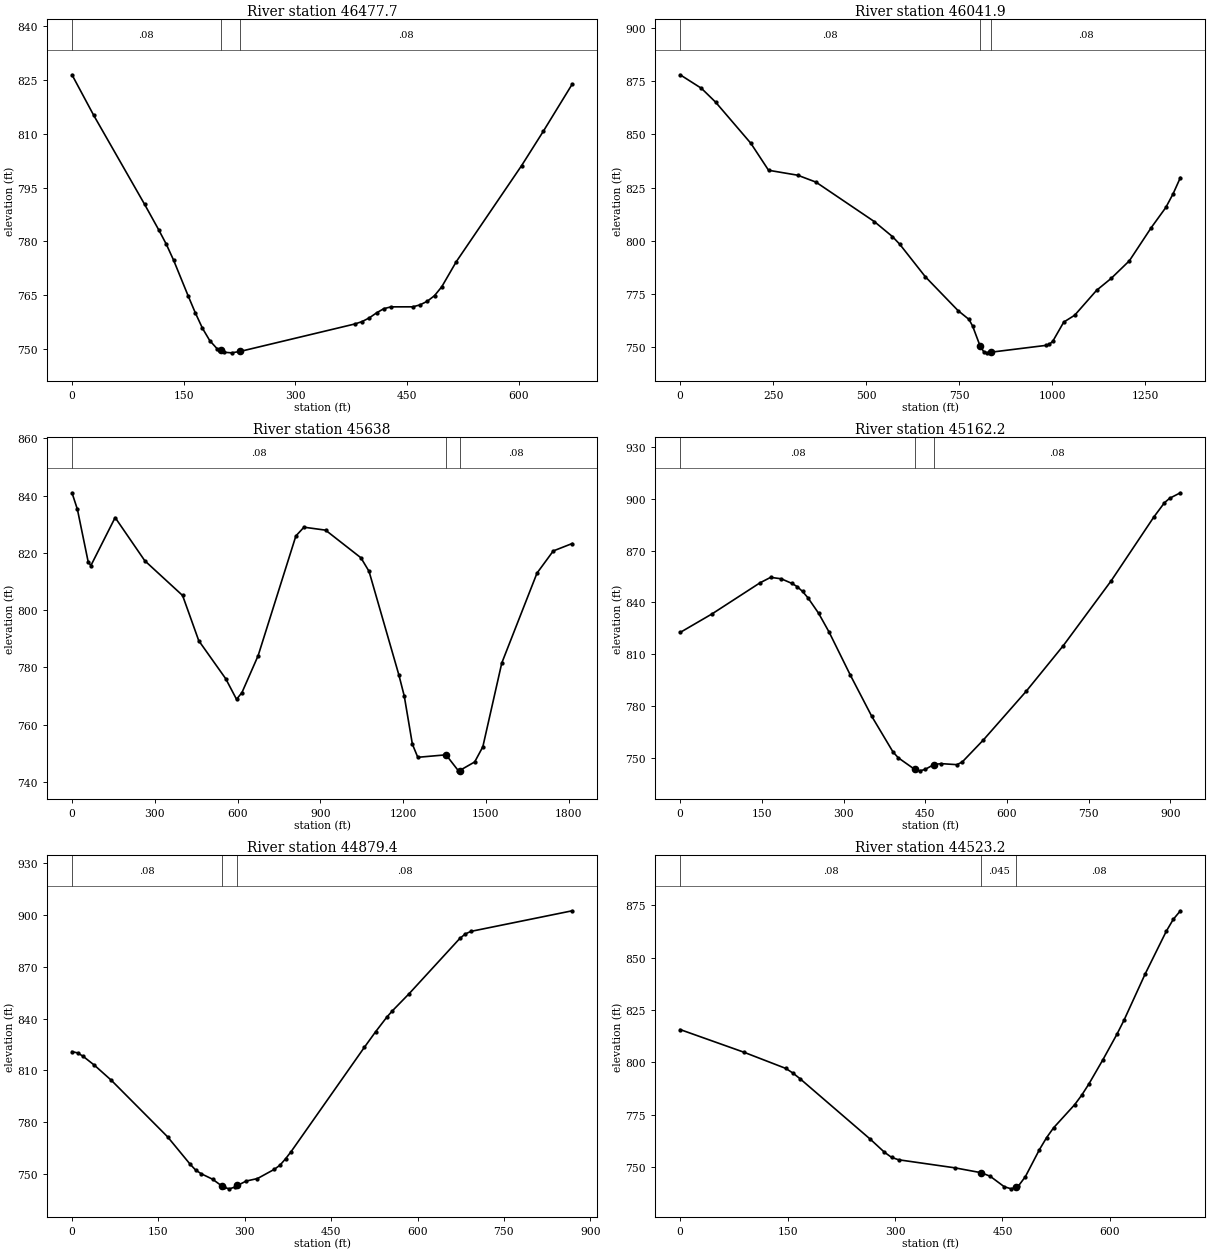
Type RM Length L Ch R = 1 ,46477.7 ,433.9,435.7,437.5
XS GIS Cut Line= 2
     1838163.601      621543.684     1837496.384      621466.112
#Sta/Elev= 30
       0  826.41    29.2  815.11    97.4  790.38   116.8  783.11   126.6  779.25
   136.3  774.86   155.8  764.95   165.5  760.18   175.2  755.84     185   752.4
   194.7  750.18   199.5749.6752   204.4  749.16   214.2     749   225.9749.3986
   379.7  757.03   389.4  757.69   399.1  758.72   408.9  760.12   418.6  761.29
   428.3   761.8   457.5  761.81   467.3  762.35     477  763.35   486.8  764.93
   496.5  767.39     516  774.38   603.6  801.09   632.8  810.66   671.7  823.82
#Mann= 3 , 0 , 0
       0     .08       0   199.5    .045       0   225.9     .08       0
Bank Sta=199.5,225.9
XS Rating Curve= 0 ,0
Exp/Cntr=0.3,0.1

Type RM Length L Ch R = 1 ,46041.9 ,414.6,403.7,398.1
XS GIS Cut Line= 3
     1838778.589      621448.749     1838636.939      621258.116
     1837548.604      621058.603
#Sta/Elev= 30
       0  878.14      57  871.78      95  865.29     190  845.83   237.5  833.14
   315.8  830.81   364.8  827.56   521.5  808.98   570.4  801.88     590  798.27
   658.6  782.98   746.7  766.99     776  762.85   785.8   759.7   805.4  750.52
   815.2  747.73     825   747.1   834.5747.3907   981.7  750.59   991.5  751.06
  1001.3  752.61  1030.6  761.59    1060  764.83  1118.8  776.56  1157.9  782.17
  1206.9  790.48  1265.6  806.09  1304.8   815.6  1324.4  822.06    1344  829.72
#Mann= 3 , 0 , 0
       0     .08       0   805.4    .045       0   834.5     .08       0
Bank Sta=805.4,834.5
XS Rating Curve= 0 ,0
Exp/Cntr=0.3,0.1

Type RM Length L Ch R = 1 ,45638   ,482.8,475.7,463.3
XS GIS Cut Line= 4
     1839245.095      620891.951     1838388.961      620557.727
     1838296.063       620613.77     1837623.398      621019.573
#Sta/Elev= 30
       0     841    19.6  835.21    58.7  816.85    68.4  815.54   156.4  832.34
     264  817.23   400.9   805.1   459.5   789.3   557.3     776   596.4  768.82
     616  771.17   674.6  784.05   811.5  825.91   840.8  828.97   919.1  827.94
  1047.2  818.28  1076.6  813.56  1184.7  777.37  1204.3  769.98  1233.8  753.13
  1253.4  748.55  1355.7749.4159  1400.7  743.82    1405743.9166  1459.6  746.93
  1489.1  752.22  1557.8   781.5  1685.5  812.93  1744.4  820.67  1813.2  823.27
#Mann= 3 , 0 , 0
       0     .08       0  1355.7    .045       0    1405     .08       0
Bank Sta=1355.7,1405
XS Rating Curve= 0 ,0
Exp/Cntr=0.3,0.1

Type RM Length L Ch R = 1 ,45162.2 ,279.3,282.7,286.1
XS GIS Cut Line= 2
     1838176.124      620139.474     1837414.271      620652.109
#Sta/Elev= 30
       0  822.62    58.6  833.38   146.5  851.35   166.1  854.53   185.6   853.7
   205.1  851.03   214.9  849.16   224.7  846.35   234.4  842.77     254  833.81
   273.5  822.77   312.6  797.78   351.7  774.04   390.8  753.35   400.5  749.99
   430.7743.2583   439.6  742.45   449.4  743.24   465.7746.0834   478.7  746.63
     508  746.03   517.8  747.57   556.8   760.4     635  788.46   703.4  815.01
   791.3  852.57   869.4  889.43     889  897.76   898.7  900.37   918.3  903.53
#Mann= 3 , 0 , 0
       0     .08       0   430.7    .045       0   465.7     .08       0
Bank Sta=430.7,465.7
XS Rating Curve= 0 ,0
Exp/Cntr=0.3,0.1

Type RM Length L Ch R = 1 ,44879.4 ,336,356.1,376.3
XS GIS Cut Line= 2
     1837860.363      620069.141     1837075.555      620441.267
#Sta/Elev= 30
       0  820.79     9.8  820.04    19.5  818.02      39  812.88    68.3  804.16
   165.9  771.39   204.9  755.56   214.7  752.06   224.5  749.92     244  746.78
   260.3742.8143   263.5  742.06   273.3  741.18     283  742.23   287.3743.1357
   302.5   745.7     322  747.14   351.3   752.5   361.1   754.9   370.8   758.6
   380.6  762.83   507.5  823.21     527  832.24   546.5  840.73   556.3  844.45
   585.6  854.48   673.4  886.45   683.1   889.1   692.9  890.56   868.6   902.5
#Mann= 3 , 0 , 0
       0     .08       0   260.3    .045       0   287.3     .08       0
Bank Sta=260.3,287.3
XS Rating Curve= 0 ,0
Exp/Cntr=0.3,0.1

Type RM Length L Ch R = 1 ,44523.2 ,407,404.3,401.6
XS GIS Cut Line= 2
     1837971.835      620049.668     1837342.177      619747.568
#Sta/Elev= 30
       0  815.63    88.5  804.86   147.5  797.05   157.4  794.84   167.2  792.18
   265.6  763.17   285.2  756.98   295.1  754.54   304.9  753.38   383.6  749.52
   420.2747.1948   432.8   745.5   452.5  740.48   462.3  739.48   469.4740.4377
   472.1   740.8     482  745.33   501.6  758.24   511.5  763.92   521.3  768.64
   550.8  779.73   560.7  784.31   570.5  789.55   590.2  801.21   609.8   813.4
   619.7  820.13   649.2  842.21   678.7  862.64   688.5  868.36   698.4  872.42
#Mann= 3 , 0 , 0
       0     .08       0   420.2    .045       0   469.4     .08       0
Bank Sta=420.2,469.4
XS Rating Curve= 0 ,0
Exp/Cntr=0.3,0.1

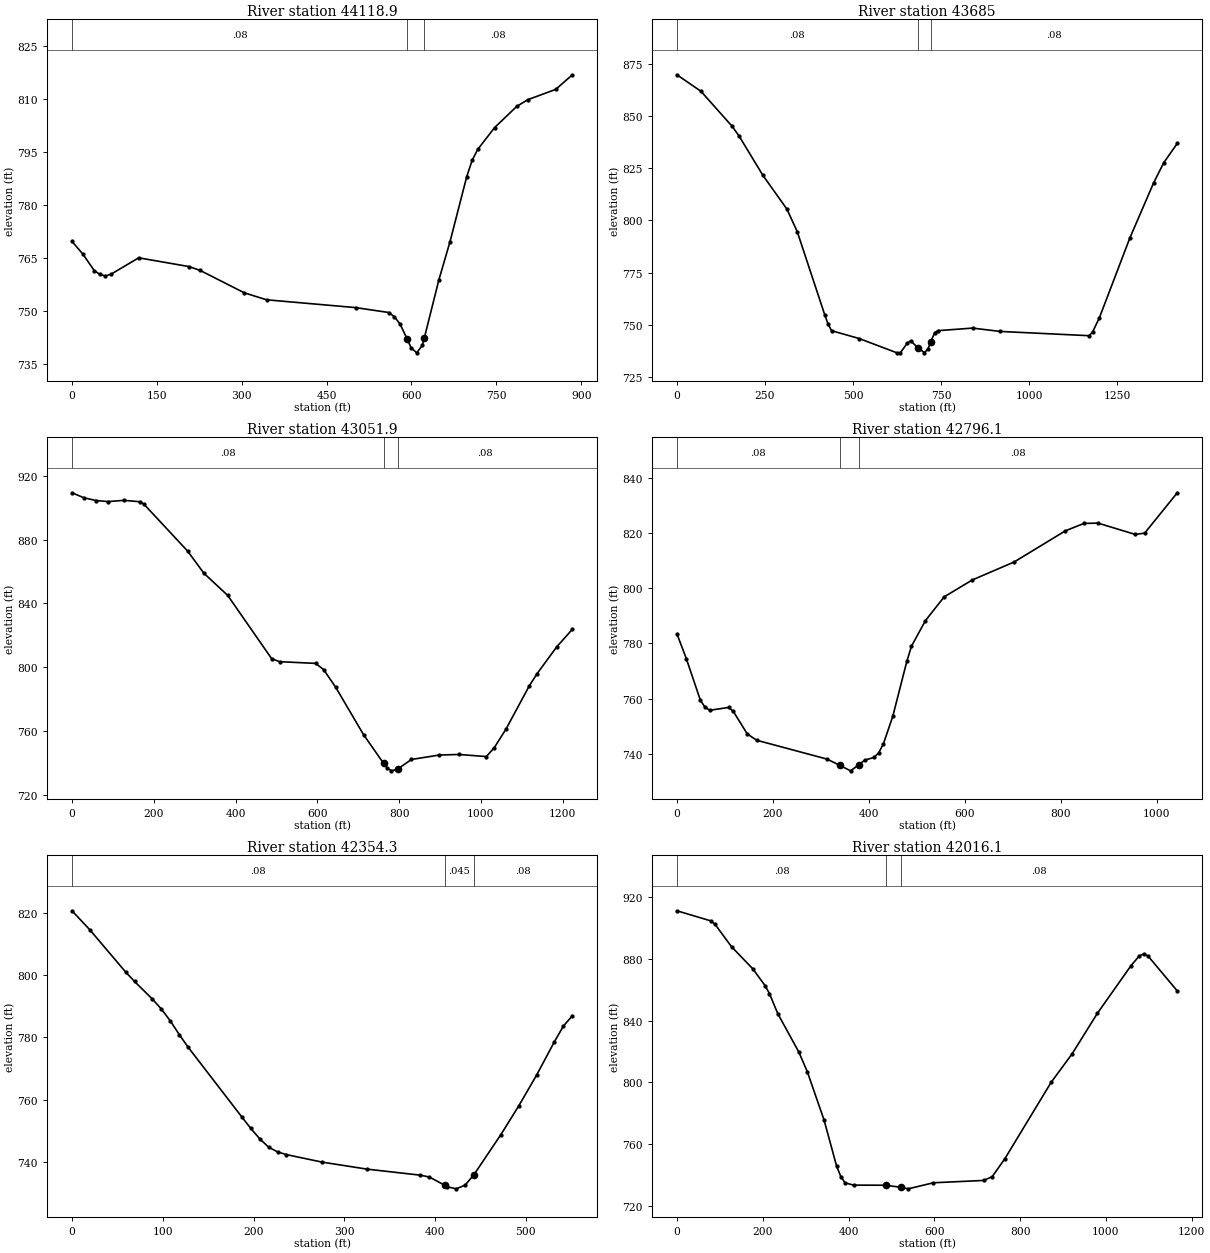
Type RM Length L Ch R = 1 ,44118.9 ,445.7,433.7,421.8
XS GIS Cut Line= 2
     1838385.192      619742.521     1837553.098      619442.985
#Sta/Elev= 30
       0  769.72    19.6  766.05    39.3  761.48    49.1   760.4      59  759.96
    68.8  760.43   117.9  765.08   206.4  762.62     226  761.56   304.6   755.2
   343.9  753.23   501.1  751.03   560.1  749.64   569.9  748.43   579.8   746.4
   592.7742.0487   599.4  739.69   609.2  738.26   619.1  740.34   622.7  742.45
   648.5  758.89   668.2  769.68   697.7     788   707.5   792.7   717.3  795.72
   746.8  801.81   786.1  807.82   805.8  809.72   854.9  812.61   884.4  816.74
#Mann= 3 , 0 , 0
       0     .08       0   592.7    .045       0   622.7     .08       0
Bank Sta=592.7,622.7
XS Rating Curve= 0 ,0
Exp/Cntr=0.3,0.1

Type RM Length L Ch R = 1 ,43685   ,668.7,633.1,597.6
XS GIS Cut Line= 3
     1838644.684      618999.866     1837560.074       619203.23
     1837316.037      619406.594
#Sta/Elev= 30
       0  869.61    68.4   861.7   156.2  845.08   175.8  840.51   244.1  821.55
   312.5  805.33   341.8  794.55   419.9  754.77   429.7  750.21   439.4  747.18
   517.6  743.45     625   736.6   634.8  736.68   654.3  741.23   664.1  742.39
   683.4739.1257   703.1  736.68   712.9  738.36   720.4741.7145   732.4  746.32
   742.2  747.22   839.8  748.44     918  746.84  1170.9   744.8  1180.5  746.54
  1199.8  753.31  1286.4  791.52  1353.8  817.84  1382.7  827.54  1421.2  836.79
#Mann= 3 , 0 , 0
       0     .08       0   683.4    .045       0   720.4     .08       0
Bank Sta=683.4,720.4
XS Rating Curve= 0 ,0
Exp/Cntr=0.3,0.1

Type RM Length L Ch R = 1 ,43051.9 ,248.6,255.8,263
XS GIS Cut Line= 3
     1837386.136      618255.735      1837543.51      619140.344
     1837309.258      619365.922
#Sta/Elev= 30
       0  909.34    29.3  906.19    58.6  904.49    87.9  903.82     127  904.59
     166  903.73   175.8  902.22   283.2  872.67   322.3  858.96   380.9  844.97
   488.3  805.33   507.8  803.46   595.7   802.4   615.3  798.52   644.6  787.54
   712.9  757.75   762.1739.7126   771.5  736.66   781.3  735.04   796.7736.2068
   830.1  742.17   898.5  744.96   946.3  745.29  1013.3  743.99  1032.4  749.46
  1061.1  761.08  1118.5   788.4  1137.6  796.01  1185.4  812.75  1223.7  823.78
#Mann= 3 , 0 , 0
       0     .08       0   762.1    .045       0   796.7     .08       0
Bank Sta=762.1,796.7
XS Rating Curve= 0 ,0
Exp/Cntr=0.3,0.1

Type RM Length L Ch R = 1 ,42796.1 ,417.9,441.9,465.8
XS GIS Cut Line= 3
     1837336.373      618755.829     1837268.585      619230.345
     1836992.634      619721.955
#Sta/Elev= 30
       0  783.48    19.6   774.5    48.9  759.43    58.7  756.86    68.5  755.79
   107.6   756.8   117.4  755.42   146.7  747.21   166.3  744.93     313   738.1
   339.4735.8541     362  733.85   379.6736.1039   391.3  737.71   410.9  738.71
   420.6  740.36   430.4  743.61     450  753.59   479.3   773.5     489     779
   518.2  788.29   557.1  796.85   615.4  802.95   702.9  809.48   809.8  820.77
   848.7  823.46   877.9  823.56   955.6  819.46   975.1  819.94  1043.1  834.55
#Mann= 3 , 0 , 0
       0     .08       0   339.4    .045       0   379.6     .08       0
Bank Sta=339.4,379.6
XS Rating Curve= 0 ,0
Exp/Cntr=0.3,0.1

Type RM Length L Ch R = 1 ,42354.3 ,364.8,338.1,311.4
XS GIS Cut Line= 2
     1837396.755      618675.265     1836883.788      618876.862
#Sta/Elev= 30
       0  820.65    19.7  814.52      59     801    68.9  797.94    88.6  792.27
    98.4  789.09   108.3  785.28   118.1  780.89     128  776.79     187  754.43
   196.8  750.79   206.7  747.41   216.5  744.73   226.4  743.18   236.2  742.31
   275.6  739.89   324.8  737.65   383.8   735.7   393.7   735.1   410.4732.5012
   413.4  731.98   423.2  731.31     433  732.49   442.7735.8311   472.4  748.71
   492.1  757.95   511.8  767.86   531.5  778.62   541.3   783.6   551.2  786.93
#Mann= 3 , 0 , 0
       0     .08       0   410.4    .045       0   442.7     .08       0
Bank Sta=410.4,442.7
XS Rating Curve= 0 ,0
Exp/Cntr=0.3,0.1

Type RM Length L Ch R = 1 ,42016.1 ,608.6,602,595.3
XS GIS Cut Line= 2
     1836830.601      618057.119     1836802.272       619223.13
#Sta/Elev= 30
       0  911.17    78.4  904.67    88.2  902.62   127.4  887.84   176.4  873.69
   205.8  862.58   215.6  857.54   235.2  844.45   284.2  819.56   303.8  806.96
     343  775.51   372.4  745.49   382.2  738.79     392  734.79   411.7  733.31
   487.5  733.24   522.7731.8517   539.1   730.9   597.9  734.84   715.5  736.35
   735.1  738.85   764.5  750.46   872.3  799.94   921.3  818.45   980.1  844.68
  1058.5  875.58  1078.1  882.03    1088  883.08  1097.8  881.98  1166.4   859.2
#Mann= 3 , 0 , 0
       0     .08       0   487.5    .045       0   522.7     .08       0
Bank Sta=487.5,522.7
XS Rating Curve= 0 ,0
Exp/Cntr=0.3,0.1

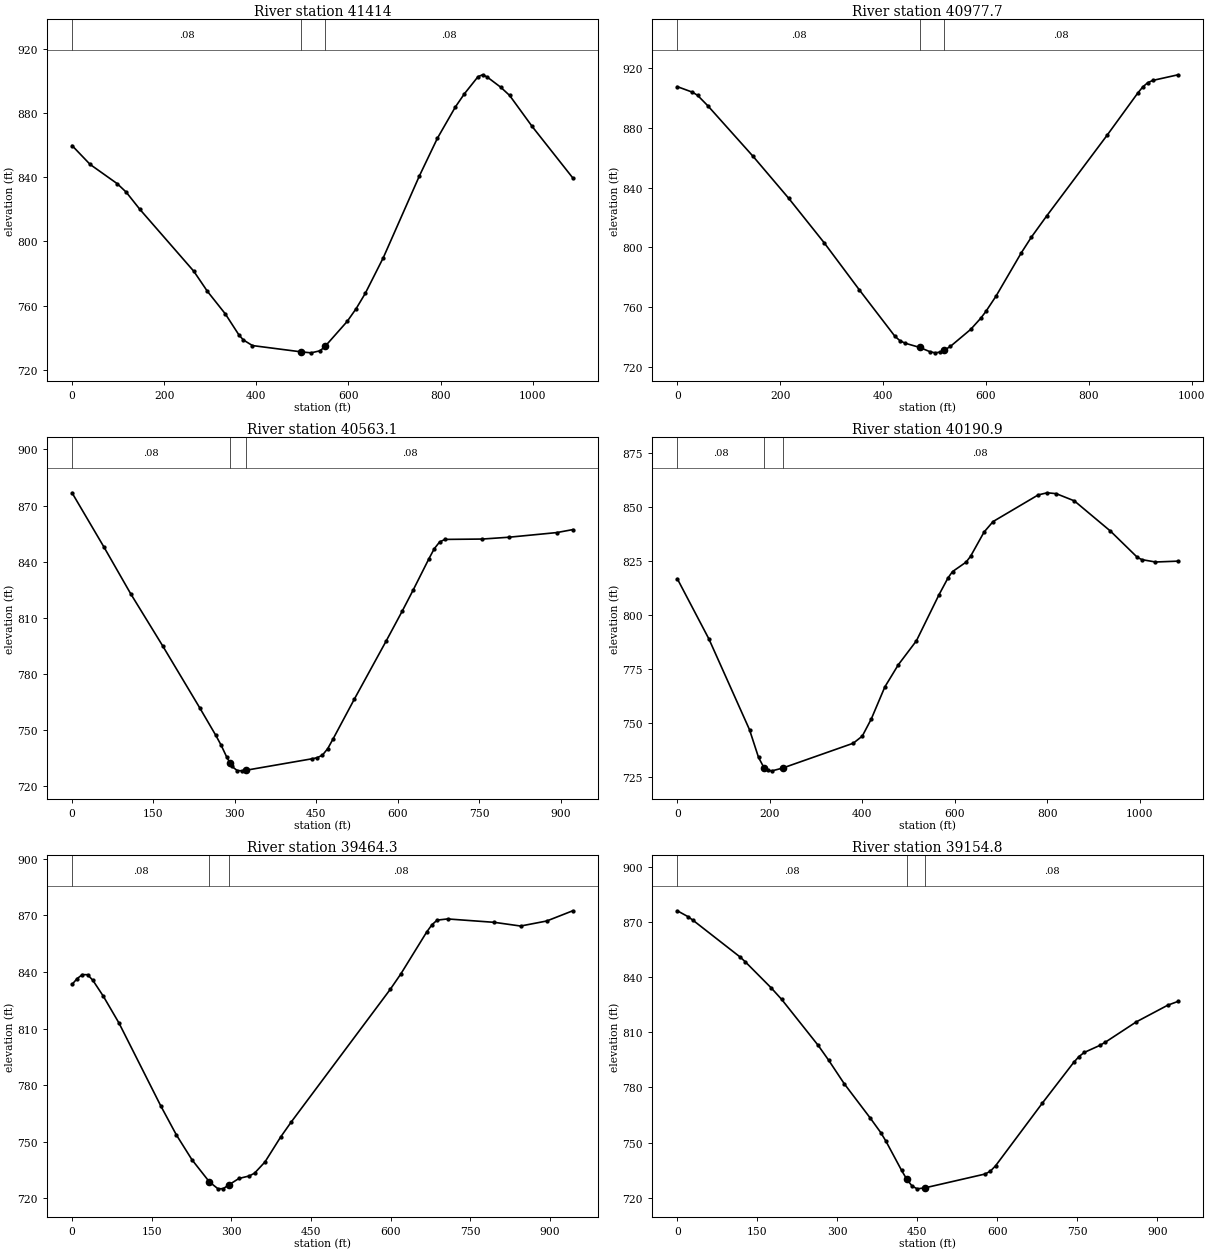
Type RM Length L Ch R = 1 ,41414   ,423.2,436.2,449.2
XS GIS Cut Line= 2
     1836303.367      618480.147     1836604.018      619524.498
#Sta/Elev= 30
       0  859.83    39.2  848.06    97.9  836.08   117.5  830.79   146.9  820.14
   264.4  781.38   293.7  768.94   332.9  754.74   362.3  741.67     372  738.53
   391.6  735.06   497.3731.1294   518.9  730.52   538.5  731.82   549.4 734.599
   597.2  750.11   616.8  758.14   636.4  767.57   675.6  789.86   753.9  840.85
     793  864.35   832.2  883.96   851.8  892.16   881.2  902.77     891  903.95
   900.7  902.64   930.1  896.27   949.7  891.09   998.6  871.75  1086.8  839.64
#Mann= 3 , 0 , 0
       0     .08       0   497.3    .045       0   549.4     .08       0
Bank Sta=497.3,549.4
XS Rating Curve= 0 ,0
Exp/Cntr=0.3,0.1

Type RM Length L Ch R = 1 ,40977.7 ,418.6,414.6,410.6
XS GIS Cut Line= 2
     1836268.486      618293.697     1835932.361      619207.485
#Sta/Elev= 30
       0  907.55    29.5  903.82    39.3  901.75      59  894.86   147.5  860.81
   216.4  832.88   285.2   803.2     354  771.48   422.9  740.54   432.7  737.55
   442.6  735.86   471.1  733.02   491.7  730.07   501.6  729.38   511.4  729.91
   518.4730.9672   531.1  733.73   570.4  745.08   590.1   752.6   599.9  757.07
   619.6   767.3   668.8  796.32   688.4  806.82   717.9  820.88     836  875.19
     895  903.14   904.8  907.28   914.6   910.2   924.5  911.72   973.6  915.49
#Mann= 3 , 0 , 0
       0     .08       0   471.1    .045       0   518.4     .08       0
Bank Sta=471.1,518.4
XS Rating Curve= 0 ,0
Exp/Cntr=0.3,0.1

Type RM Length L Ch R = 1 ,40563.1 ,365.8,371.3,376.8
XS GIS Cut Line= 2
     1835783.439      618260.859     1835671.176      619176.411
#Sta/Elev= 30
       0  876.81    58.9  847.76   107.9  822.91   166.8  795.05   235.5  761.71
     265  747.05   274.8  741.78   284.6  735.74   291.4  732.15   294.4  730.56
   304.2  728.31     314  728.14   321.1728.4877   441.6  734.56   451.4  735.15
   461.2  736.51     471  739.99   480.8  745.15   520.1   766.5     579  797.73
   608.4  813.61     628  824.57   657.5  841.58   667.3   846.9   677.1   850.5
   686.9  851.88   755.6  852.07   804.6  853.04     893  855.53   922.4  857.12
#Mann= 3 , 0 , 0
       0     .08       0   291.4    .045       0   321.1     .08       0
Bank Sta=291.4,321.1
XS Rating Curve= 0 ,0
Exp/Cntr=0.3,0.1

Type RM Length L Ch R = 1 ,40190.9 ,690,726.3,762.5
XS GIS Cut Line= 2
     1835446.553      618399.758     1835088.977      619421.938
#Sta/Elev= 30
       0  816.79    68.3  788.97   156.1  747.02   175.6  734.21   187.6729.3639
   195.1  728.15   204.9  727.99   227.5729.2541   380.5  740.76     400  744.05
   419.5  751.99   448.8   766.8     478  777.07   517.1  788.13   565.8  809.37
   585.4   817.2   595.1  820.11   624.4  824.48   634.1  827.16   663.4  838.41
   682.9  843.26   780.5  855.58     800  856.56   819.5  856.15   858.5  852.83
   936.6  838.86   995.1  826.65  1004.9  825.64  1034.1  824.55  1082.9  824.95
#Mann= 3 , 0 , 0
       0     .08       0   187.6    .045       0   227.5     .08       0
Bank Sta=187.6,227.5
XS Rating Curve= 0 ,0
Exp/Cntr=0.3,0.1

Type RM Length L Ch R = 1 ,39464.3 ,319.1,309.5,299.8
XS GIS Cut Line= 2
     1835496.811      618364.832     1834629.911      617995.003
#Sta/Elev= 30
       0  833.37     9.8  836.49    19.6  838.58    29.4  838.49    39.3  835.51
    58.9  827.13    88.4  812.91   166.9  769.12   196.4  753.69   225.8  740.51
   258.7728.7469   274.9  725.11   284.7  725.22   295.3727.2442   314.2   730.6
   333.8  731.95   343.6  733.42   363.2  739.35   392.7  752.56   412.3  760.39
   598.9  830.72   618.5  838.74   667.6  861.12   677.4  864.93   687.2  867.42
   706.9  868.04   795.2  866.23   844.3  864.28   893.4  866.94   942.5  872.36
#Mann= 3 , 0 , 0
       0     .08       0   258.7    .045       0   295.3     .08       0
Bank Sta=258.7,295.3
XS Rating Curve= 0 ,0
Exp/Cntr=0.3,0.1

Type RM Length L Ch R = 1 ,39154.8 ,223.4,221.8,220.2
XS GIS Cut Line= 2
     1835766.403      617948.841     1834827.679      617972.073
#Sta/Elev= 30
       0  876.01    19.6  872.89    29.3  870.88   117.4  850.96   127.2  848.35
   176.1  834.08   195.6  827.86   264.1  802.86   283.7  794.82     313     782
   361.9   763.3   381.5  755.44   391.2  750.77   420.6  734.87   430.4  730.02
   440.2  726.38   449.9  724.87   464.5 725.422   577.1  732.92   586.9  734.44
   596.7  737.36   684.7  771.54   743.4  793.63   753.2  796.77     763  798.99
   792.3  802.84   802.1  804.48   860.8  815.64   919.4  824.65     939  826.77
#Mann= 3 , 0 , 0
       0     .08       0   430.4    .045       0   464.5     .08       0
Bank Sta=430.4,464.5
XS Rating Curve= 0 ,0
Exp/Cntr=0.3,0.1