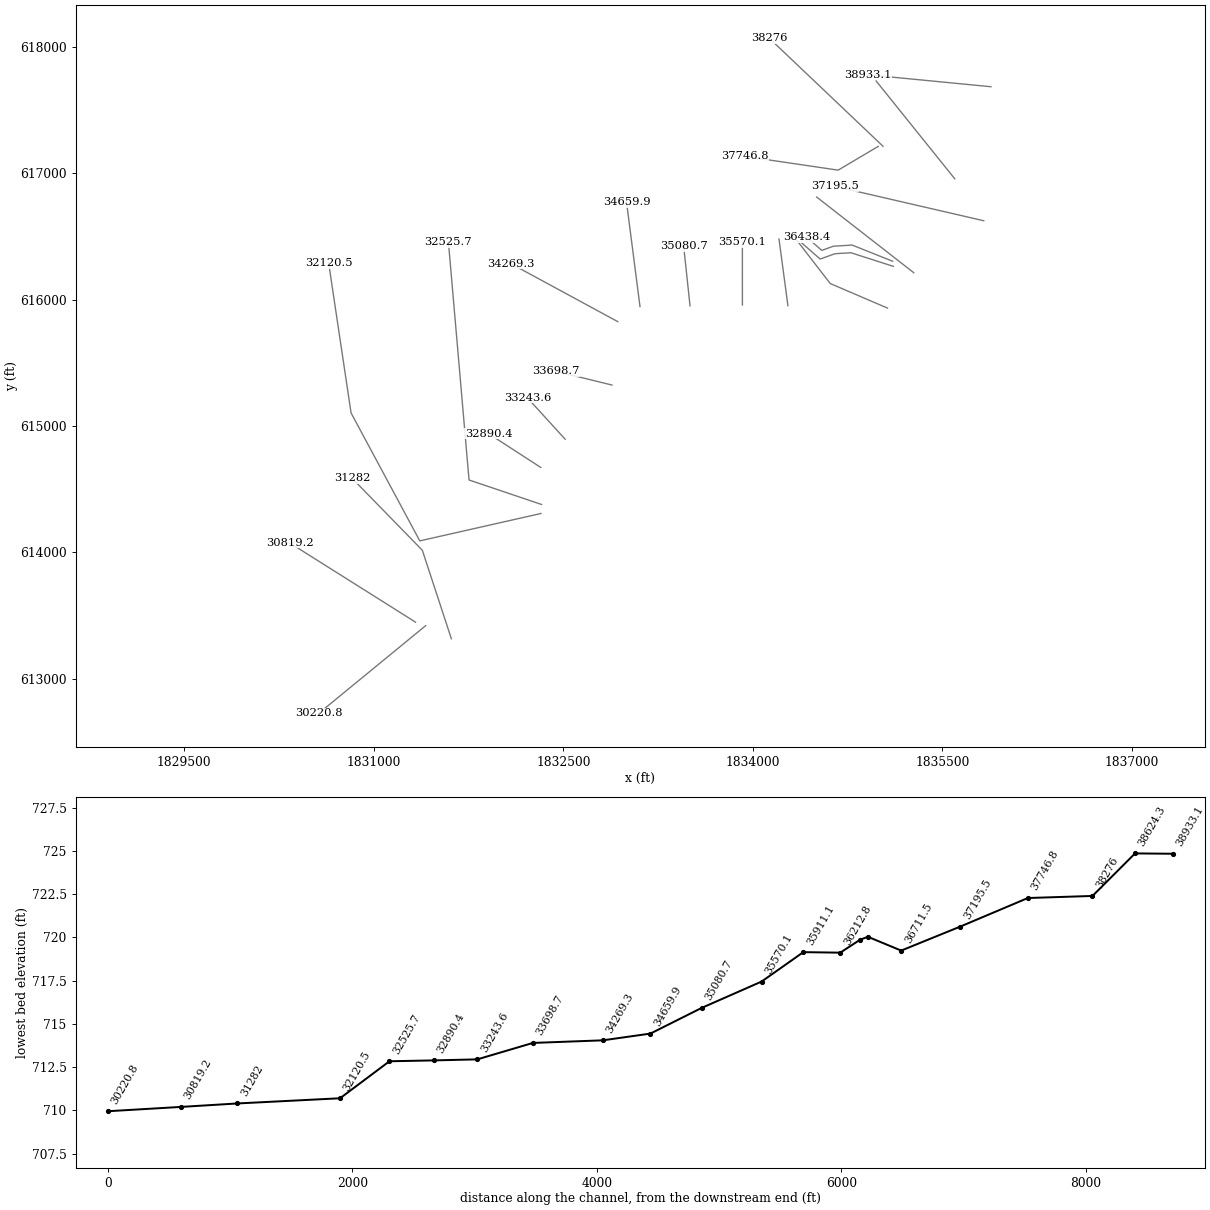
HEC-RAS study FlatFork.prj: FlatFork

--- FlatFork.g01 (geometry) --- (continued)

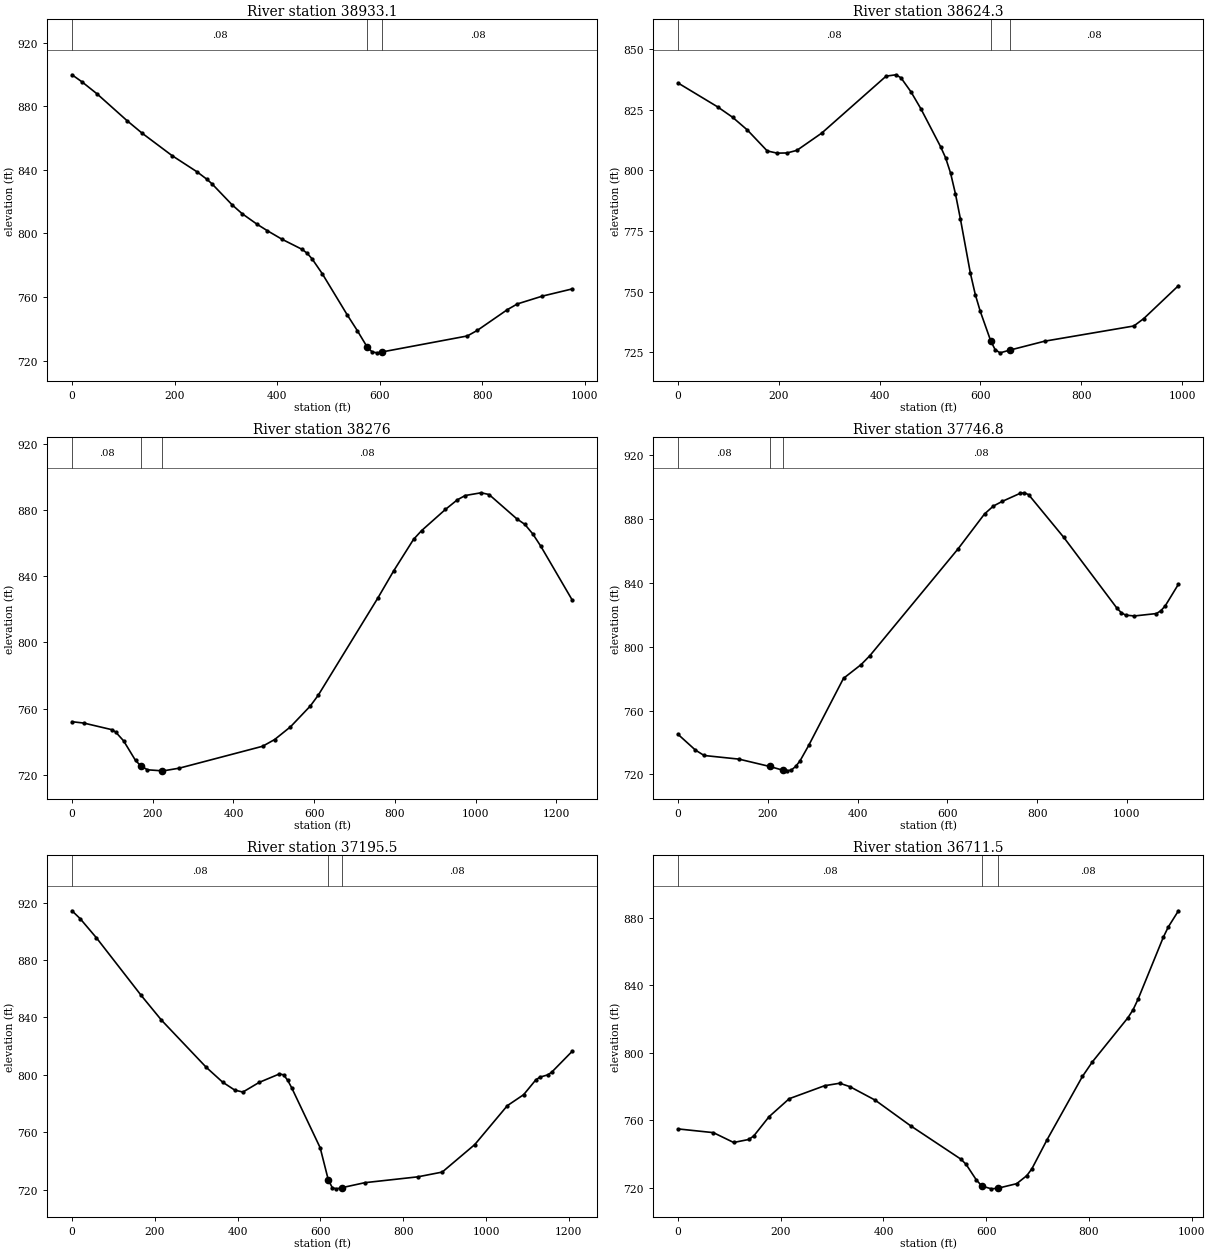
Type RM Length L Ch R = 1 ,38933.1 ,326.5,308.4,290.3
XS GIS Cut Line= 2
     1835883.386      617682.613     1834911.882      617776.865
#Sta/Elev= 30
       0  899.91    19.5  895.46    48.8  887.91   107.4  871.01   136.6  863.18
   195.2  849.01     244  838.78   263.5  834.03   273.3  831.17   312.3  818.03
   331.9  812.44   361.1  805.78   380.7   801.8     410  796.29     449  789.96
   458.8   787.5   468.5  783.92     488  774.74   536.8  748.76   556.4  738.88
   575.9  728.41   585.6  725.37   595.4  724.84   605.6725.4517   771.1  735.47
   790.6  738.98   849.2  752.04   868.7  755.64   917.5  760.56   976.1  765.12
#Mann= 3 , 0 , 0
       0     .08       0   575.9    .045       0   605.6     .08       0
Bank Sta=575.9,605.6
XS Rating Curve= 0 ,0
Exp/Cntr=0.3,0.1

Type RM Length L Ch R = 1 ,38624.3 ,341,348.1,355.2
XS GIS Cut Line= 2
     1835597.101      616954.462     1834974.862      617728.165
#Sta/Elev= 30
       0     836    78.6  826.16   108.1  821.91   137.6  816.63     177  808.01
   196.6  807.11   216.3  807.18   235.9  808.26   285.1  815.36   412.9  838.82
   432.5  839.38   442.4  838.12     462  832.42   481.7  825.44     521  809.74
   530.8  805.24   540.7  798.94   550.5  790.28   560.3  779.98     580   757.7
   589.8  748.87   599.7  741.94   620.3729.8448   629.2  726.15     639  724.86
   658.1725.9691   727.4  729.66   904.4  735.92   924.1  738.98   992.9  752.53
#Mann= 3 , 0 , 0
       0     .08       0   620.3    .045       0   658.1     .08       0
Bank Sta=620.3,658.1
XS Rating Curve= 0 ,0
Exp/Cntr=0.3,0.1

Type RM Length L Ch R = 1 ,38276   ,504.1,528.6,553.2
XS GIS Cut Line= 2
     1835029.334      617211.848      1834130.24      618065.281
#Sta/Elev= 30
       0  752.09    29.5  751.26    98.4  747.29   108.2  745.83   127.9   740.5
   157.4  728.65   170.7725.3513   186.9  723.03   223.2722.4063   226.3   722.4
   265.6  724.01   472.2  737.26   501.8  741.29   541.1  748.98   590.3  761.58
     610  768.12   757.6  826.83   796.9  843.28   846.1  862.31   865.8  867.53
   924.8  880.33   954.3  886.14     974  888.78  1013.4  890.43    1033  889.38
  1101.9  874.68  1121.6  871.36  1141.3   865.6  1160.9  858.27  1239.6  825.38
#Mann= 3 , 0 , 0
       0     .08       0   170.7    .045       0   223.2     .08       0
Bank Sta=170.7,223.2
XS Rating Curve= 0 ,0
Exp/Cntr=0.3,0.1

Type RM Length L Ch R = 1 ,37746.8 ,568.5,552.1,535.7
XS GIS Cut Line= 3
     1834991.533      617210.815     1834674.254      617023.039
     1833935.892      617131.733
#Sta/Elev= 30
       0  745.12    38.8  735.26    58.2  731.88   135.8  729.61   204.2725.0219
     235 722.567   242.6  722.28   252.3  722.76     262     725   271.7  728.46
   291.1  738.16   368.7  780.16     408  788.77   427.6  794.39     624   861.2
   682.9  883.02   702.6  887.96   722.2  890.86   761.5  895.83   771.3  896.27
   781.1  895.11   859.7  868.29   977.5  824.23   987.3  821.33   997.2  819.72
  1016.8  819.19  1065.9   820.7  1075.7  822.44  1085.5   825.5    1115  839.08
#Mann= 3 , 0 , 0
       0     .08       0   204.2    .045       0     235     .08       0
Bank Sta=204.2,235
XS Rating Curve= 0 ,0
Exp/Cntr=0.3,0.1

Type RM Length L Ch R = 1 ,37195.5 ,489.4,483.7,475.8
XS GIS Cut Line= 2
     1835826.505      616622.797     1834648.542      616894.576
#Sta/Elev= 30
       0   914.3    19.7  908.82      59  895.47   167.1  855.36   216.2  838.11
   324.3  805.28   363.7  794.98   393.1  789.41   412.8  788.04   452.1  794.76
   501.2  800.67   511.1  800.01   520.9  796.31   530.7  791.01   599.5  749.25
   619.2  726.81     629  721.34   638.8  720.63   652.5721.4715   707.6  724.93
   835.4  728.99   894.4  732.31     973  751.48  1051.6  778.56    1091  786.21
  1120.4  796.52  1130.3  798.42  1149.9  800.06  1159.8  802.17  1208.9   816.6
#Mann= 3 , 0 , 0
       0     .08       0   619.2    .045       0   652.5     .08       0
Bank Sta=619.2,652.5
XS Rating Curve= 0 ,0
Exp/Cntr=0.3,0.1

Type RM Length L Ch R = 1 ,36711.5 ,250.8,272.9,295.5
XS GIS Cut Line= 2
     1835272.897      616211.731     1834504.079      616810.305
#Sta/Elev= 30
       0  754.79    68.9  752.58   108.3  746.74   137.8  748.53   147.6  750.66
   177.2  762.02   216.5  772.71   285.4  780.42   314.9  781.89   334.6  779.87
   383.8  771.87   452.7  756.68   551.2  736.76     561  733.72   580.7  724.59
   591.5720.9103   610.2  719.24   622.8719.5942   659.4   722.3   679.1  727.07
   688.9  731.08   718.5  748.34   787.4  785.91     807  794.65   875.9  820.71
   885.8  825.35   895.6  831.64   944.8  868.42   954.7  874.66   974.4   884.2
#Mann= 3 , 0 , 0
       0     .08       0   591.5    .045       0   622.8     .08       0
Bank Sta=591.5,622.8
XS Rating Curve= 0 ,0
Exp/Cntr=0.3,0.1

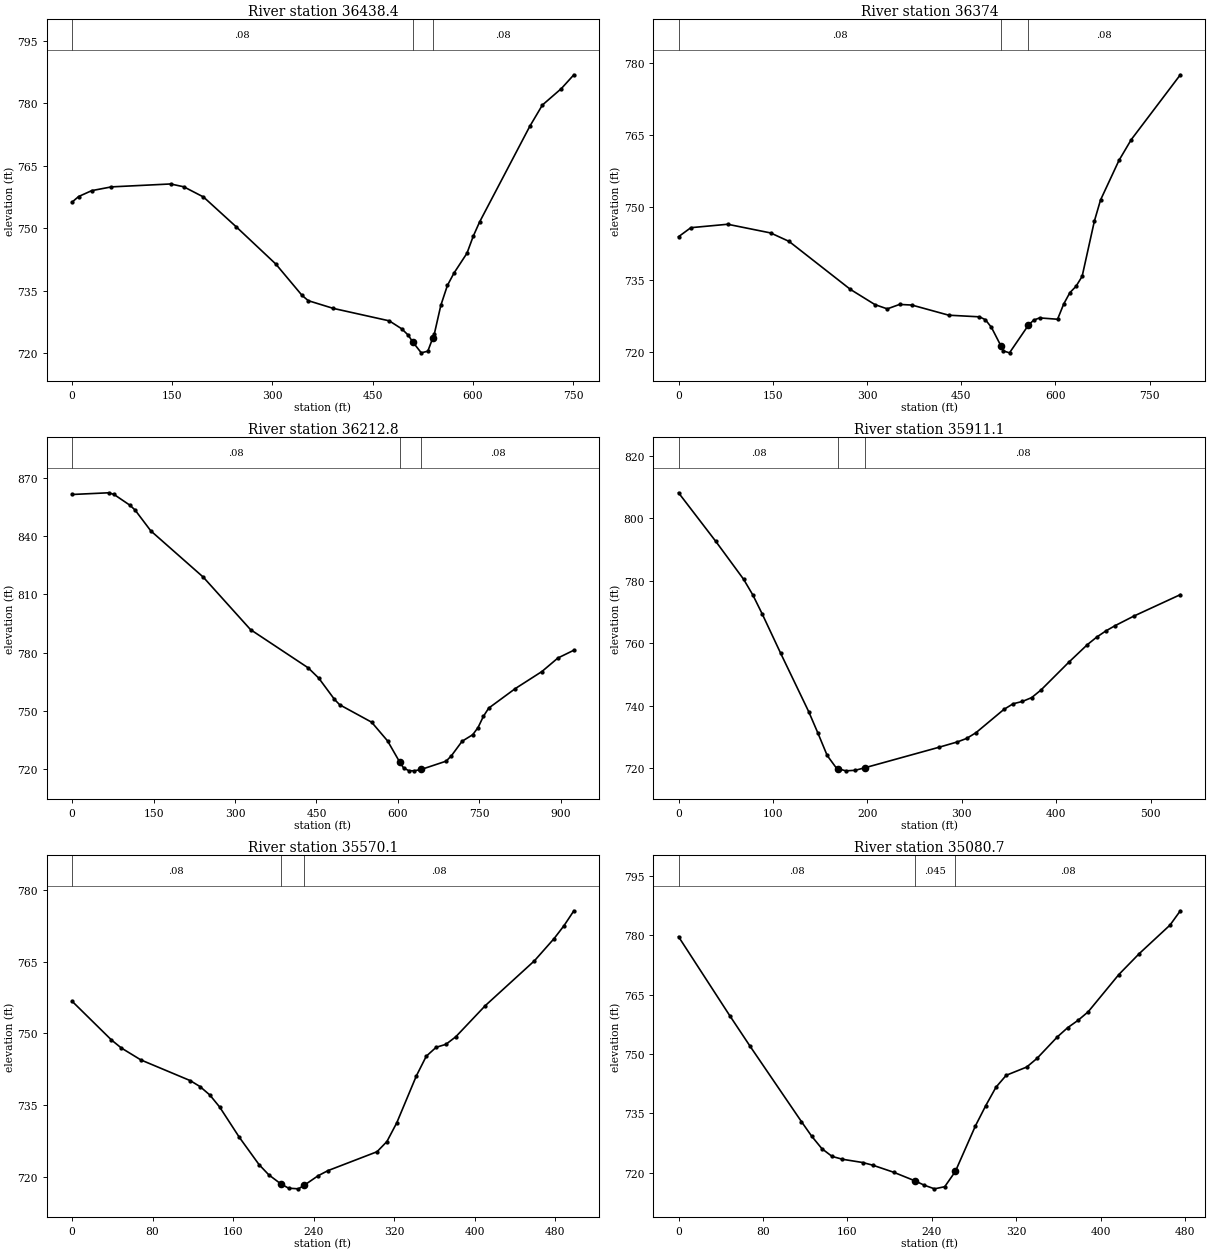
Type RM Length L Ch R = 1 ,36438.4 ,68.3,65,63.5
XS GIS Cut Line= 5
     1835105.191      616302.587     1834785.557       616430.44
     1834636.656      616421.416     1834544.764      616388.335
     1834424.346      616493.701
#Sta/Elev= 30
       0  756.27     9.8  757.62    29.5  759.04      59  759.94   147.5  760.64
   167.2  759.96   196.7  757.51   245.9  750.31   304.9   741.4   344.3  733.84
   353.6  732.58   390.9  730.73   474.8  727.73   493.4  725.82   503.2  724.29
   509.7722.7048   522.7  720.04   532.5  720.44   539.9 723.596   542.3  724.62
     552  731.47   561.8  736.24   571.6   739.2   591.1  743.99   600.5  748.08
   609.9  751.47   685.2  774.52     704  779.62   732.3  783.56   751.1  786.89
#Mann= 3 , 0 , 0
       0     .08       0   509.7    .045       0   539.9     .08       0
Bank Sta=509.7,539.9
XS Rating Curve= 0 ,0
Exp/Cntr=0.3,0.1

Type RM Length L Ch R = 1 ,36374   ,189.2,160.3,131.4
XS GIS Cut Line= 5
     1835110.763      616262.197     1834775.761      616369.736
     1834648.879      616362.047     1834531.844      616319.914
     1834384.836      616448.546
#Sta/Elev= 30
       0  743.92    19.6  745.79    78.2   746.5   146.6   744.7   175.9  742.95
   273.6     733   312.8  729.84   332.3  728.97   351.8  729.89   371.4  729.76
   430.1  727.66     479  727.32   488.5  726.72   498.1  725.12   513.1 721.316
   517.2  720.25   526.8  719.86   556.8725.5739   565.1  726.62   574.6   727.1
   603.3  726.82   613.1  729.98   622.9  732.33   632.6  733.63   642.4   735.7
   661.9  747.16   671.7  751.53     701  759.72   720.6  764.04   798.7  777.47
#Mann= 3 , 0 , 0
       0     .08       0   513.1    .045       0   556.8     .08       0
Bank Sta=513.1,556.8
XS Rating Curve= 0 ,0
Exp/Cntr=0.3,0.1

Type RM Length L Ch R = 1 ,36212.8 ,314.2,302.1,290
XS GIS Cut Line= 3
     1835064.799      615932.093     1834611.812      616126.217
     1834348.066      616467.355
#Sta/Elev= 30
       0   861.3    67.6  862.18    77.3  861.31   106.3  855.82     116  853.32
     145  842.58   241.6  818.78   328.6  791.78   434.8  772.11   454.2  766.84
   483.2  755.88   492.8  753.11   551.6  744.15     581  734.51   603.4723.5828
   610.4  720.64   620.2  719.18     630  719.12   642.8719.8249   688.8   724.1
   698.6  726.91   718.2  734.34   737.8  737.72   747.6  741.41   757.4  747.14
   767.2  751.39   816.2  761.45   865.2  770.22   894.6  777.17     924  781.18
#Mann= 3 , 0 , 0
       0     .08       0   603.4    .045       0   642.8     .08       0
Bank Sta=603.4,642.8
XS Rating Curve= 0 ,0
Exp/Cntr=0.3,0.1

Type RM Length L Ch R = 1 ,35911.1 ,344.1,341,338
XS GIS Cut Line= 2
     1834276.786       615951.41     1834206.353      616478.047
#Sta/Elev= 30
       0  808.11    39.4  792.58    68.9  780.44    78.7   775.4    88.6  769.34
   108.2  756.72   137.8   738.1   147.6  731.21   157.4  724.06   167.3  719.97
   169.2719.8113   177.1  719.15     187  719.32   197.3720.1354   275.5  726.67
   295.2   728.4     305  729.51   314.9  731.34   344.4  738.78   354.2   740.6
   364.1  741.35   373.9  742.58   383.7  744.99   413.2  753.89   432.9  759.53
   442.8  761.94   452.6  763.94   462.4  765.62   482.1  768.66   531.3  775.52
#Mann= 3 , 0 , 0
       0     .08       0   169.2    .045       0   197.3     .08       0
Bank Sta=169.2,197.3
XS Rating Curve= 0 ,0
Exp/Cntr=0.3,0.1

Type RM Length L Ch R = 1 ,35570.1 ,486.7,488.9,491.2
XS GIS Cut Line= 2
     1833916.687      615956.361     1833916.462      616454.735
#Sta/Elev= 30
       0  756.74    39.1  748.63    48.9  746.95    68.4  744.44   117.3  740.12
     127  738.88   136.8  737.11   146.6  734.58   166.1  728.25   185.7  722.53
   195.4  720.38   207.2718.5136     215  717.59   224.8  717.45   230.8718.2307
   244.3  720.18   254.1  721.26   302.9  725.22   312.7  727.35   322.5  731.28
     342  741.12   351.8  745.22   361.6  747.09   371.3  747.71   381.1  749.29
   410.4  755.81   459.3  765.22   478.8  769.87   488.6  772.56   498.4  775.68
#Mann= 3 , 0 , 0
       0     .08       0   207.2    .045       0   230.8     .08       0
Bank Sta=207.2,230.8
XS Rating Curve= 0 ,0
Exp/Cntr=0.3,0.1

Type RM Length L Ch R = 1 ,35080.7 ,420.2,420.8,421.4
XS GIS Cut Line= 2
     1833502.167       615950.22     1833451.781      616422.688
#Sta/Elev= 30
       0   779.6    48.5  759.66    67.9  751.88   116.4   732.9   126.1  729.22
   135.8  726.06   145.4  724.12   155.2   723.4   174.5  722.57   184.2  721.88
   203.6  720.13   223.8717.9602   232.7  716.85   242.4  715.93   252.1  716.47
   262.2 720.347   281.2  731.85   290.9  736.92   300.6  741.58   310.3   744.6
   329.7  746.68   339.4  748.85   358.8  754.31   368.5  756.62   378.2  758.45
   387.9  760.62     417  770.05   436.4  775.35   465.4  782.52   475.2  786.14
#Mann= 3 , 0 , 0
       0     .08       0   223.8    .045       0   262.2     .08       0
Bank Sta=223.8,262.2
XS Rating Curve= 0 ,0
Exp/Cntr=0.3,0.1

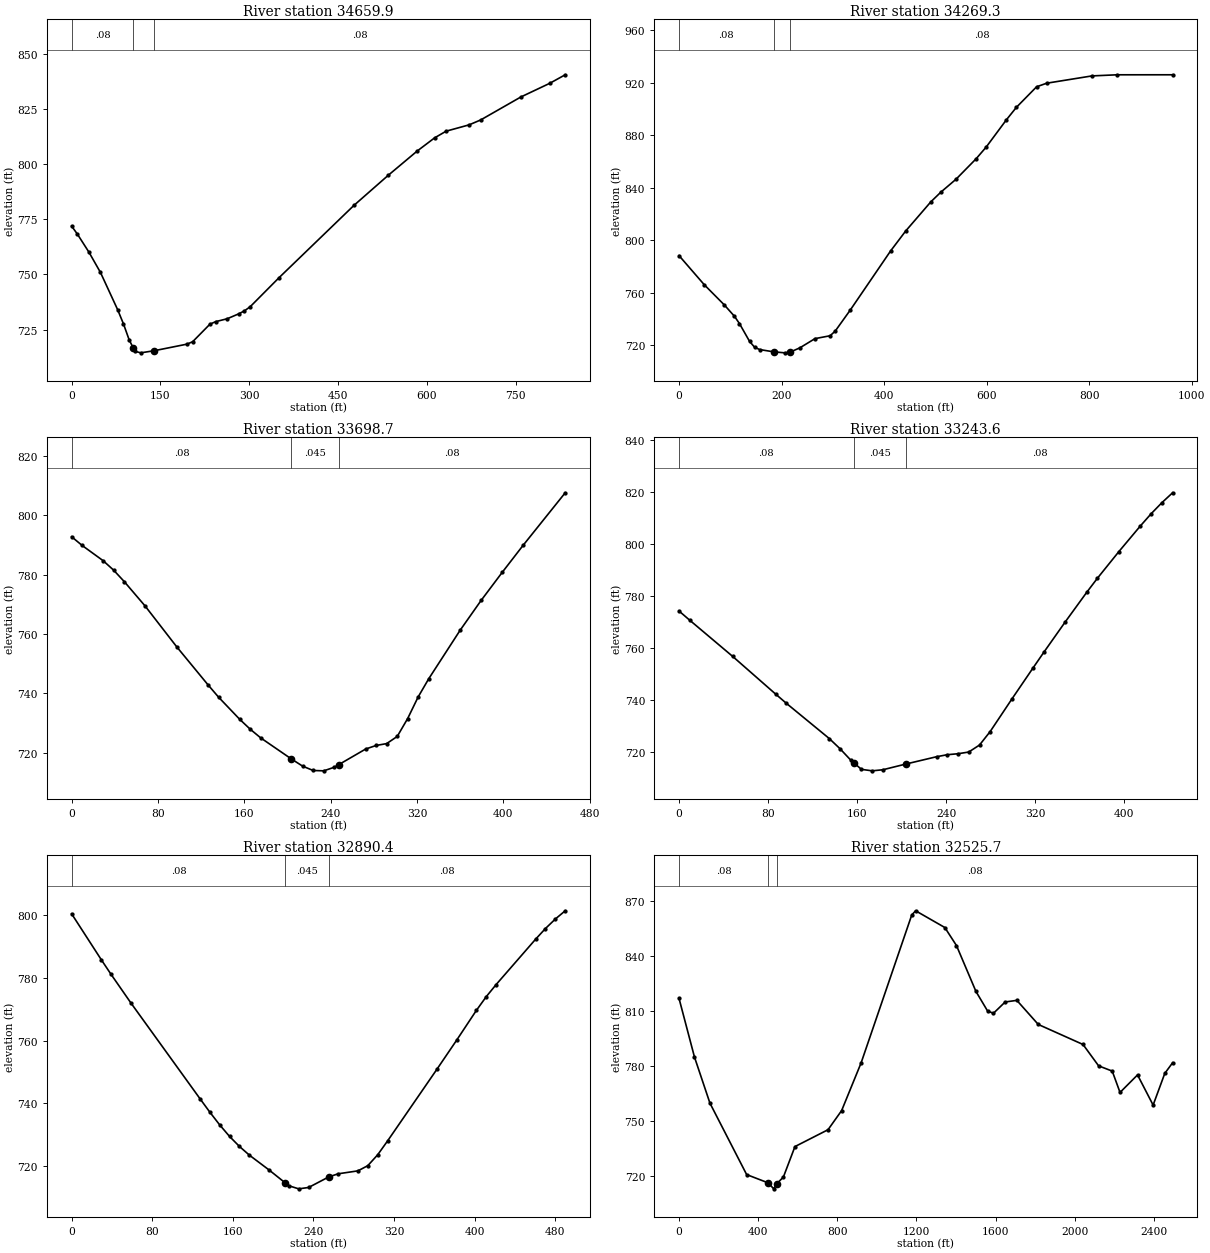
Type RM Length L Ch R = 1 ,34659.9 ,368.6,390.1,411.5
XS GIS Cut Line= 3
     1833106.321      615944.355     1833000.424      616764.886
     1832999.578      616771.445
#Sta/Elev= 30
       0  771.84     9.7  768.22    29.2  760.05    48.7  750.85    77.9  733.88
    87.6  727.52    97.3  720.23   104.4716.5278   107.1  715.12   116.8  714.44
   139.8715.4149   194.7  718.37   204.4  719.46   233.6  727.41   243.3  728.57
   262.8  729.88   282.3  732.11     292  733.47   301.7  735.34   350.4  748.48
   476.9  781.22   535.3  794.96     584   805.9   613.2  811.82   632.7  814.86
   671.6  817.73   691.1  819.95   759.2  830.38   807.9  836.56     834  840.42
#Mann= 3 , 0 , 0
       0     .08       0   104.4    .045       0   139.8     .08       0
Bank Sta=104.4,139.8
XS Rating Curve= 0 ,0
Exp/Cntr=0.3,0.1

Type RM Length L Ch R = 1 ,34269.3 ,564.9,570.5,576
XS GIS Cut Line= 2
     1832930.511      615824.905     1832084.042      616283.596
#Sta/Elev= 30
       0  788.22    49.1  766.06    88.4  750.58   108.1  741.95   117.9  736.36
   137.5  722.86   147.4  718.32   157.2  716.56   184.3714.8354   206.3  714.05
   217.1714.6534   235.8  717.89   265.2  724.89   294.7  727.08   304.6   730.6
     334  746.66   412.6  791.72   442.1  806.97   491.2  829.23   510.8  836.64
   540.3  846.47   579.6  862.11   599.3  871.08   638.6  891.81   658.2  901.36
   697.5     917   717.2  919.73   805.6   925.3   854.7  926.15   962.8  926.16
#Mann= 3 , 0 , 0
       0     .08       0   184.3    .045       0   217.1     .08       0
Bank Sta=184.3,217.1
XS Rating Curve= 0 ,0
Exp/Cntr=0.3,0.1

Type RM Length L Ch R = 1 ,33698.7 ,468.3,455.1,442.1
XS GIS Cut Line= 2
       1832884.4      615323.644      1832440.22      615432.663
#Sta/Elev= 30
       0  792.83     9.7   789.9    29.2  784.75    38.9  781.57    48.7  777.73
    68.1  769.47    97.3  755.75   126.5  742.84   136.2  738.72   155.7  731.29
   165.4  727.96   175.2  725.01   203.4717.9598   214.1  715.47   223.8  714.02
   233.6   713.9   243.3   715.1   247.6716.0043   272.5  721.26   282.2  722.46
   291.9  723.08   301.7  725.49   311.4  731.54   321.1  738.81   330.9  744.94
     360   761.3   379.5  771.38     399  780.82   418.4  789.95   457.4  807.66
#Mann= 3 , 0 , 0
       0     .08       0   203.4    .045       0   247.6     .08       0
Bank Sta=203.4,247.6
XS Rating Curve= 0 ,0
Exp/Cntr=0.3,0.1

Type RM Length L Ch R = 1 ,33243.6 ,347.2,353.2,359.2
XS GIS Cut Line= 2
     1832514.235      614895.211     1832215.225      615222.812
#Sta/Elev= 30
       0  774.35     9.6  770.82    48.2  756.91    86.8  742.44    96.4  738.91
     135  725.36   144.6  721.47   154.3  717.07   156.9716.1085   163.9  713.52
   173.6  712.95   183.2  713.37   204.3715.6138   231.4  718.37   241.1  719.15
   250.7  719.52   260.3  720.17     270  722.86   279.6  728.05   298.9  740.42
   318.2  752.54   327.8   758.5   347.1   770.2   366.4  781.56     376  786.97
   395.3  797.21   414.6  807.05   424.3  811.75   433.9  815.97   443.5  819.77
#Mann= 3 , 0 , 0
       0     .08       0   156.9    .045       0   204.3     .08       0
Bank Sta=156.9,204.3
XS Rating Curve= 0 ,0
Exp/Cntr=0.3,0.1

Type RM Length L Ch R = 1 ,32890.4 ,359.1,364.7,370.4
XS GIS Cut Line= 2
     1832321.329      614671.941     1831909.978      614938.111
#Sta/Elev= 30
       0  800.23    29.4  785.67    39.2  780.98    58.8  771.94   127.4  741.52
   137.2  737.24     147  733.19   156.8  729.52   166.6  726.35   176.4   723.6
     196  718.88   212.2714.7374   215.6  713.87   225.4  712.89   235.2  713.32
   255.3 716.683   264.6  717.67   284.2   718.6     294  720.25   303.8   723.7
   313.6  728.09   362.6  750.86   382.2   760.1   401.8  769.57   411.6  773.93
   421.4  777.77   460.6  792.18   470.4  795.58   480.2  798.59     490  801.21
#Mann= 3 , 0 , 0
       0     .08       0   212.2    .045       0   255.3     .08       0
Bank Sta=212.2,255.3
XS Rating Curve= 0 ,0
Exp/Cntr=0.3,0.1

Type RM Length L Ch R = 1 ,32525.7 ,391.5,404.5,417.5
XS GIS Cut Line= 3
     1832327.332       614379.18     1831753.569      614572.751
     1831590.303      616455.125
#Sta/Elev= 30
       0  816.73    78.1  784.74   156.3  759.58   341.8  720.62   451.5716.0606
   478.6  712.84     494715.6364   527.4  719.23     586   735.9   753.2   745.1
     822  755.54   920.4  781.55  1176.3  862.23    1196  864.56  1343.6  855.43
  1402.6  845.57    1501  820.54  1560.1  809.81  1589.6  808.65  1648.7   814.8
  1707.7  815.68    1816  802.54  2042.3   791.6    2121  779.95  2189.9  777.08
  2229.3  765.44  2317.8     775  2396.6  758.54  2455.6  775.84    2495  781.63
#Mann= 3 , 0 , 0
       0     .08       0   451.5    .045       0     494     .08       0
Bank Sta=451.5,494
XS Rating Curve= 0 ,0
Exp/Cntr=0.3,0.1

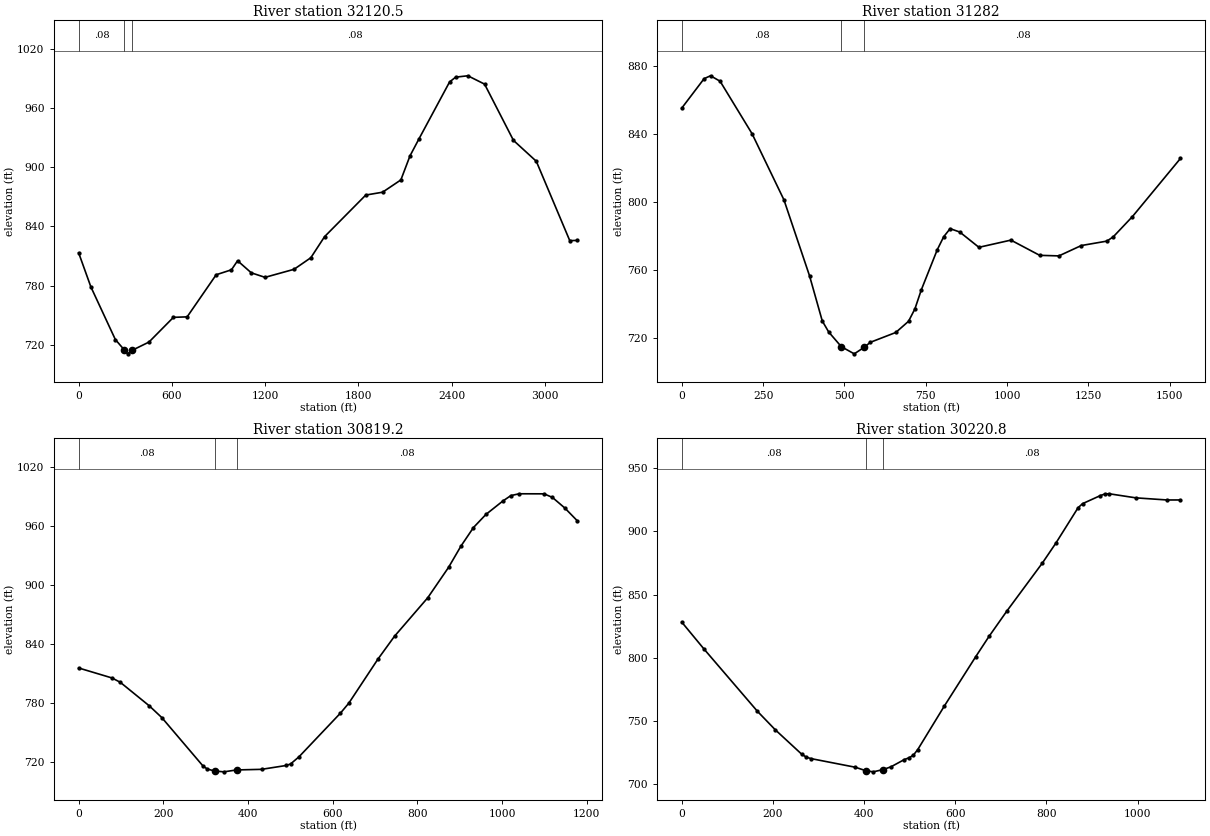
Type RM Length L Ch R = 1 ,32120.5 ,871.7,838.4,805.1
XS GIS Cut Line= 4
       1832322.7      614307.916     1831363.864      614091.249
     1830820.062      615103.036     1830642.972      616286.423
#Sta/Elev= 30
       0   813.1    78.6  778.59   235.9  725.23   293.6714.6796   314.6   710.7
   346.1714.4427   452.2  722.63   609.5  747.71   697.9  748.22   884.7  790.93
     983  795.95  1022.3  805.13  1110.6  792.87    1199  788.29  1385.5  796.45
  1493.5  808.18  1581.9  829.55    1847  871.76    1955  874.64  2072.8  887.11
  2131.7  911.58  2190.4  929.09  2386.2  986.49  2425.3  991.36  2503.6  992.75
  2611.3  984.29  2797.3  927.18  2944.1  906.03  3159.4   825.5  3208.4  825.79
#Mann= 3 , 0 , 0
       0     .08       0   293.6    .045       0   346.1     .08       0
Bank Sta=293.6,346.1
XS Rating Curve= 0 ,0
Exp/Cntr=0.3,0.1

Type RM Length L Ch R = 1 ,31282   ,447.2,462.6,478
XS GIS Cut Line= 3
     1831613.755      613317.196     1831384.075      614016.708
     1830827.821      614586.869
#Sta/Elev= 30
       0  855.34    68.7  872.71    88.4  874.41   117.8   871.2     216  840.26
   314.1  801.21   392.7  756.43   431.9  729.78   451.6  723.29   490.4714.6271
   530.1   710.4   561.4714.3271   579.2  717.17   657.7  722.99     697   729.6
   716.6  736.92   736.2  748.11   785.4  771.85   805.1  779.48   824.8  784.23
   854.3  782.27   913.3  773.23  1011.6  777.48  1100.1   768.5  1159.1  768.17
    1228  774.28  1306.6  776.89  1326.3  779.44  1385.3   791.4  1532.8  825.66
#Mann= 3 , 0 , 0
       0     .08       0   490.4    .045       0   561.4     .08       0
Bank Sta=490.4,561.4
XS Rating Curve= 0 ,0
Exp/Cntr=0.3,0.1

Type RM Length L Ch R = 1 ,30819.2 ,570.1,598.5,626.9
XS GIS Cut Line= 2
     1831330.149      613448.557     1830333.371      614075.879
#Sta/Elev= 30
       0  815.77    78.5  805.66    98.2  801.26   166.8  777.28   196.3  765.38
   294.4  715.75   304.2  713.02   320.9711.0478   342.9   710.2     373  712.13
   431.8  712.74   490.7   716.7   500.5  718.24   520.2  725.42   618.3  769.91
     638  780.01   706.6  824.69   745.9  848.03   824.4  887.16   873.5  918.02
   902.9  939.73   932.4  958.56   961.8  971.85  1001.1  985.28  1020.7  991.03
  1040.4  992.86  1099.2   992.8  1118.9  989.13  1148.3  978.31  1177.8   965.3
#Mann= 3 , 0 , 0
       0     .08       0   320.9    .045       0     373     .08       0
Bank Sta=320.9,373
XS Rating Curve= 0 ,0
Exp/Cntr=0.3,0.1

Type RM Length L Ch R = 1 ,30220.8 ,463,416.1,487.5
XS GIS Cut Line= 2
     1831410.155      613420.657     1830563.702      612727.219
#Sta/Elev= 30
       0  828.29    48.8  807.02   166.1  757.77   205.2  743.18   263.8  723.67
   273.6  721.54   283.3  720.43     381  713.57   403.7710.8472   420.1  709.95
   442.2711.7686   459.2  713.96   488.5  719.68   498.3  721.02     508  723.05
   517.8  727.58   576.4  762.13   644.8  800.88   674.1  816.97   713.2     837
   791.4   875.1   820.7  890.67   869.5  918.69   879.3  921.91   918.4   928.3
   928.1  929.55   937.9  929.73   996.5   926.5  1064.9  924.83  1094.2  924.85
#Mann= 3 , 0 , 0
       0     .08       0   403.7    .045       0   442.2     .08       0
Bank Sta=403.7,442.2
XS Rating Curve= 0 ,0
Exp/Cntr=0.3,0.1