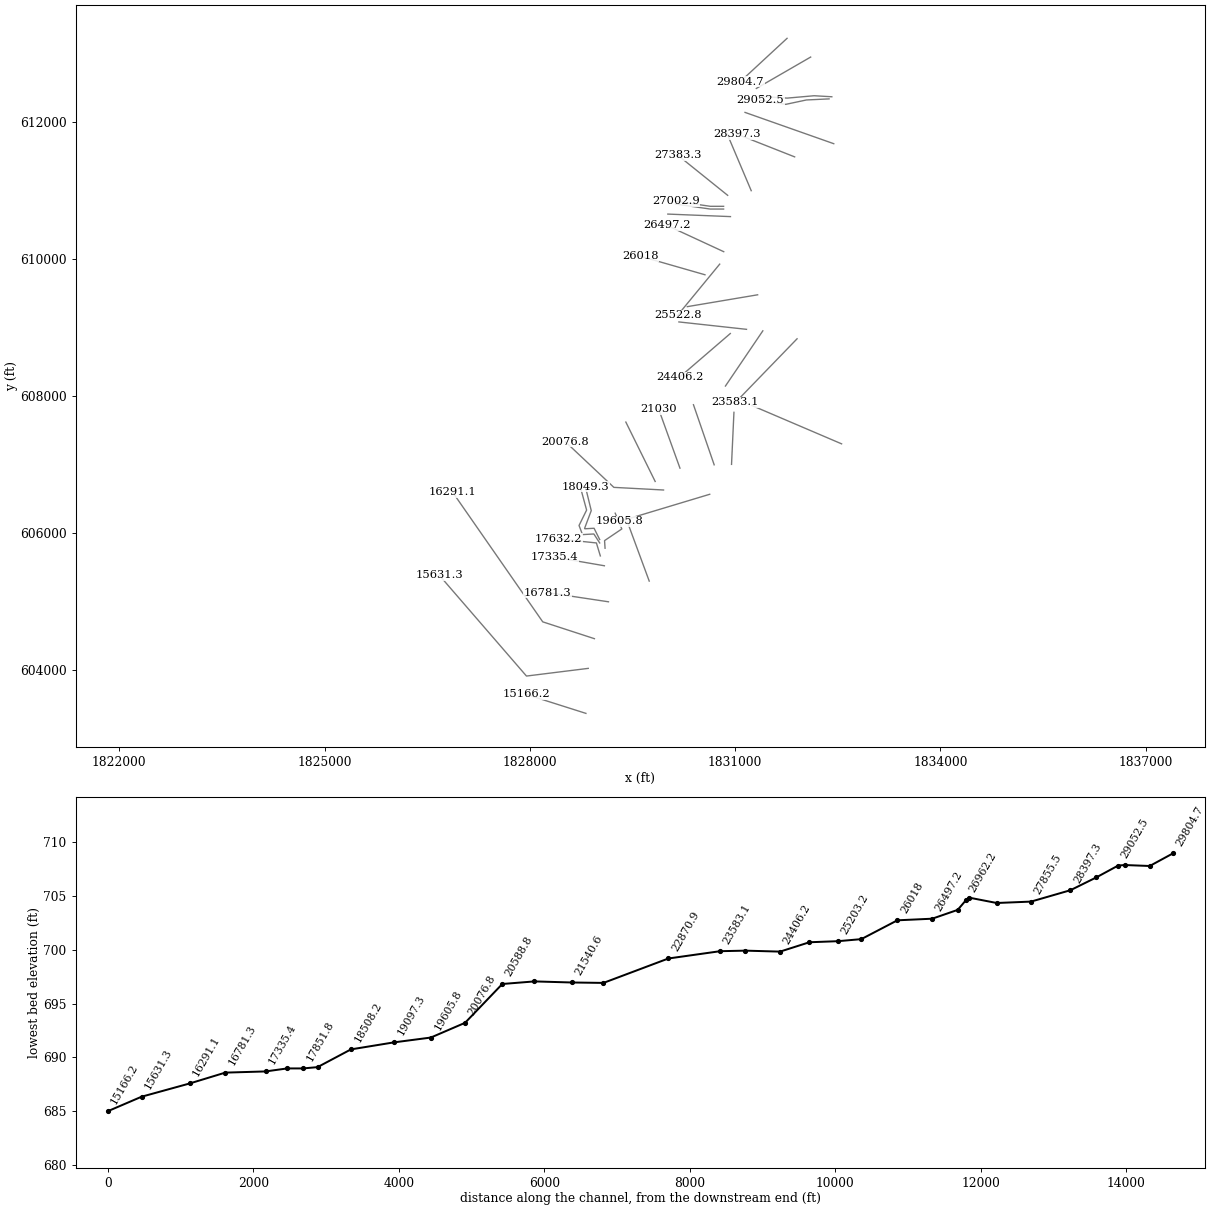
HEC-RAS study FlatFork.prj: FlatFork

--- FlatFork.g01 (geometry) --- (continued)

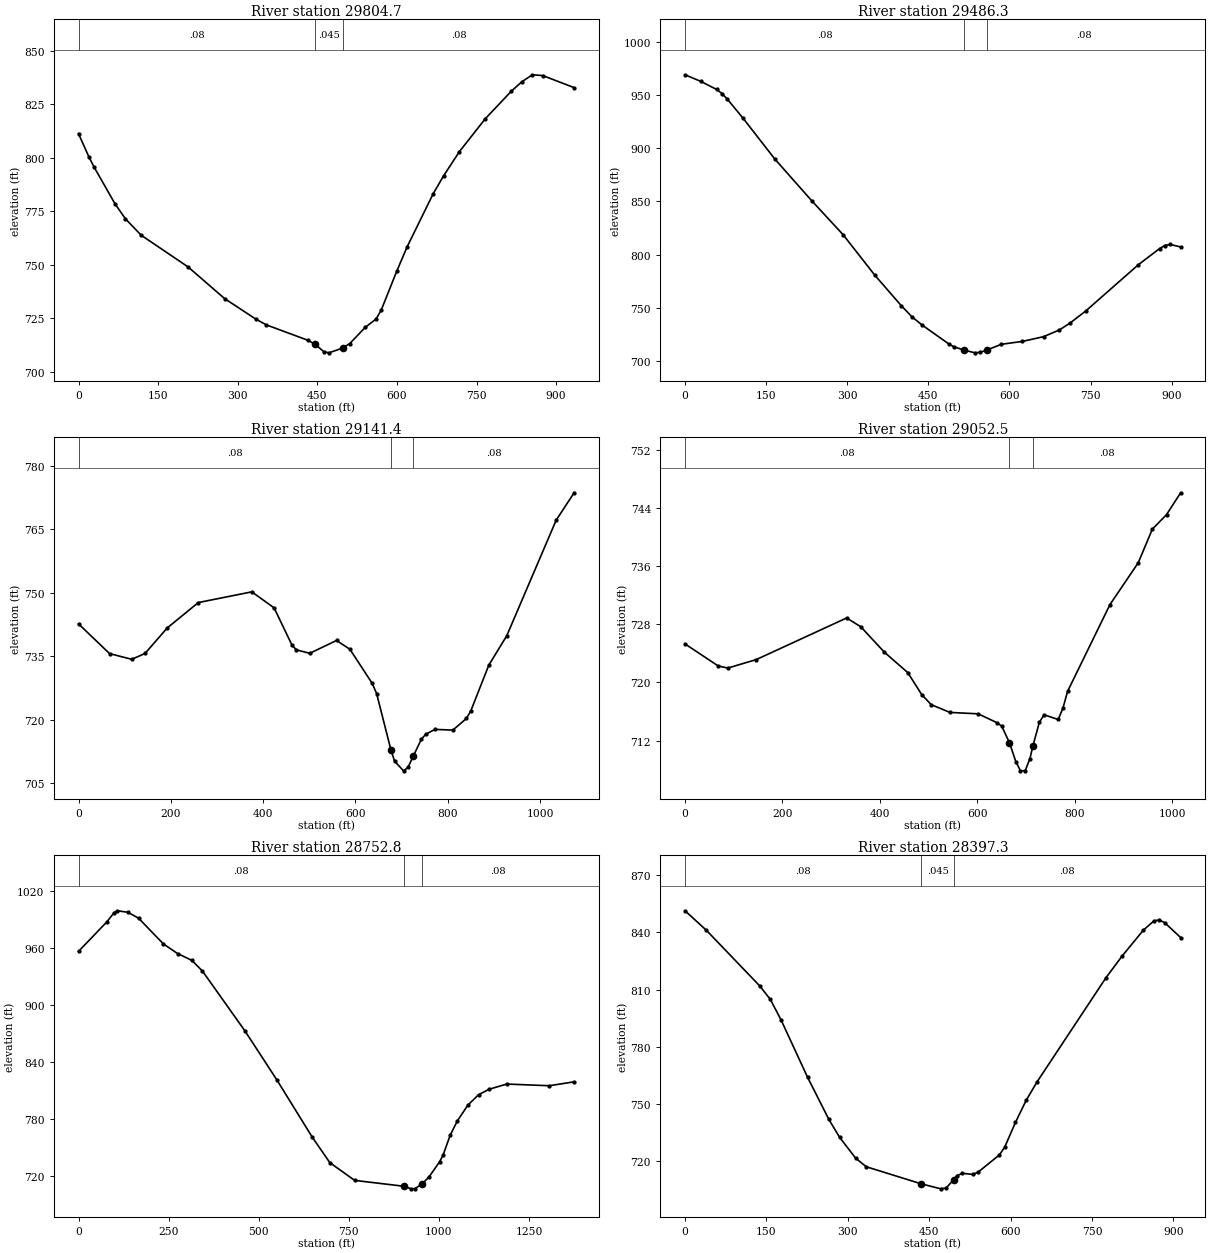
Type RM Length L Ch R = 1 ,29804.7 ,325.5,318.4,313.3
XS GIS Cut Line= 2
     1831759.683      613224.552     1831074.046      612590.609
#Sta/Elev= 30
       0  811.27    19.7  800.38    29.5  795.62    68.8  778.51    88.5   771.5
     118  763.89   206.4  749.08   275.2  734.31   334.2  724.69   353.9  722.02
   432.5  714.81   446.3712.8804     462  709.55   471.8  708.97   497.8  711.21
   511.1   713.3   540.6  720.95   560.3  724.66   570.1  728.75   599.6  747.06
   619.3  758.52   668.4  783.28   688.1  791.67   717.6  802.87   766.7  818.31
   815.8  831.17   835.5  835.52   855.2  838.76   874.8  838.39   933.8  832.76
#Mann= 3 , 0 , 0
       0     .08       0   446.3    .045       0   497.8     .08       0
Bank Sta=446.3,497.8
XS Rating Curve= 0 ,0
Exp/Cntr=0.3,0.1

Type RM Length L Ch R = 1 ,29486.3 ,358.3,345,331.6
XS GIS Cut Line= 2
     1832104.652      612951.083     1831310.785      612492.754
#Sta/Elev= 30
       0  968.94    29.3  962.69    58.5  955.12    68.3  951.34      78  946.18
   107.3  928.19   165.8  889.97     234  850.84   292.6  818.61   351.1  780.66
   399.8  752.23   419.3  741.82   438.8  733.81   487.6  716.25   497.3  713.48
   515.8710.4249   536.4   707.8   546.1  708.31   557.7710.3231   585.1  715.82
   624.1  718.54   663.1  722.98   692.4  729.29   711.9  735.69   741.1  747.06
   838.7  790.64   877.7  805.69   887.4   808.6   897.2  809.59   916.7  807.26
#Mann= 3 , 0 , 0
       0     .08       0   515.8    .045       0   557.7     .08       0
Bank Sta=515.8,557.7
XS Rating Curve= 0 ,0
Exp/Cntr=0.3,0.1

Type RM Length L Ch R = 1 ,29141.4 ,91,88.9,86.8
XS GIS Cut Line= 4
     1832414.179      612371.083     1832155.053      612386.105
     1831760.566      612351.367     1831343.175      612378.473
#Sta/Elev= 30
       0  742.62    67.3  735.59   115.4  734.24   144.2  735.63   192.3  741.66
   259.6  747.65   375.5  750.18   423.8   746.4   462.4  737.62   472.1  736.47
     501  735.66     559  738.69     588  736.62   636.3  728.57   645.9  726.15
   676.9712.8482   684.8  710.18   704.2  707.89   713.9   708.7     725711.2871
   743.1  715.41   752.8  716.57   772.3  717.68   811.2  717.52   840.4  720.26
   850.1  722.09     889  732.87   927.9  739.81  1034.9  767.11  1073.8  773.59
#Mann= 3 , 0 , 0
       0     .08       0   676.9    .045       0     725     .08       0
Bank Sta=676.9,725
XS Rating Curve= 0 ,0
Exp/Cntr=0.3,0.1

Type RM Length L Ch R = 1 ,29052.5 ,303.8,299.7,295.6
XS GIS Cut Line= 4
      1832373.85      612340.094     1832042.406      612324.311
     1831740.574      612260.158     1831368.244      612319.801
#Sta/Elev= 30
       0  725.29    68.3  722.25    87.8  721.97   146.4  723.14   331.8  728.86
   360.8  727.65     409  724.17   457.2  721.35   486.1  718.31   505.4  716.94
     544  715.87   601.8  715.68   640.4  714.46   650.1  713.99     666711.7209
   679.1  709.11   688.7  707.84   698.4  707.86   708.1  709.53   714.3711.2867
   727.4  714.51   737.1  715.55   766.1   714.9   775.8  716.44   785.4  718.77
   872.4   730.7   930.4  736.44   959.5  741.08   988.5  743.06  1017.5  746.07
#Mann= 3 , 0 , 0
       0     .08       0     666    .045       0   714.3     .08       0
Bank Sta=666,714.3
XS Rating Curve= 0 ,0
Exp/Cntr=0.3,0.1

Type RM Length L Ch R = 1 ,28752.8 ,356.2,355.4,354.6
XS GIS Cut Line= 2
     1832442.213      611685.544     1831145.238      612142.636
#Sta/Elev= 30
       0  956.63    78.6  987.71    98.2  997.13     108  999.38   137.5  997.78
     167  991.44   235.7  964.43     275  954.34   314.3  947.24   343.8  935.99
   461.7  873.02   550.1  821.56   648.3  761.32   697.4   734.3   766.2  715.64
   902.3709.4828   923.3  706.74   933.2  706.82   953.1  711.85   972.4  719.16
  1001.9  735.17  1011.7  742.31  1031.4  763.23    1051   778.1  1080.5  794.87
    1110  805.75  1139.4  811.57  1188.5  817.02  1306.4  815.25  1375.2  819.37
#Mann= 3 , 0 , 0
       0     .08       0   902.3    .045       0   953.1     .08       0
Bank Sta=902.3,953.1
XS Rating Curve= 0 ,0
Exp/Cntr=0.3,0.1

Type RM Length L Ch R = 1 ,28397.3 ,559.5,541.8,524.1
XS GIS Cut Line= 2
     1831870.445      611493.186     1831020.829       611828.08
#Sta/Elev= 30
       0  851.38    39.3  841.16   137.5  812.01   157.1  804.93   176.8  794.21
   225.8  764.06   265.1  741.92   284.8  732.58   314.2  721.69   333.9  717.14
   435.3708.1674   471.4  705.55   481.2  706.01   495.1710.3917   500.8  712.41
   510.6  713.69   530.3  713.11   540.1  714.32   579.4  723.38   589.2  727.54
   608.8  740.36   628.5  751.93   648.1  761.41   775.8  816.35   805.2  827.58
   844.5  841.22   864.1  846.09     874  846.57   883.8  845.13   913.2  837.36
#Mann= 3 , 0 , 0
       0     .08       0   435.3    .045       0   495.1     .08       0
Bank Sta=435.3,495.1
XS Rating Curve= 0 ,0
Exp/Cntr=0.3,0.1

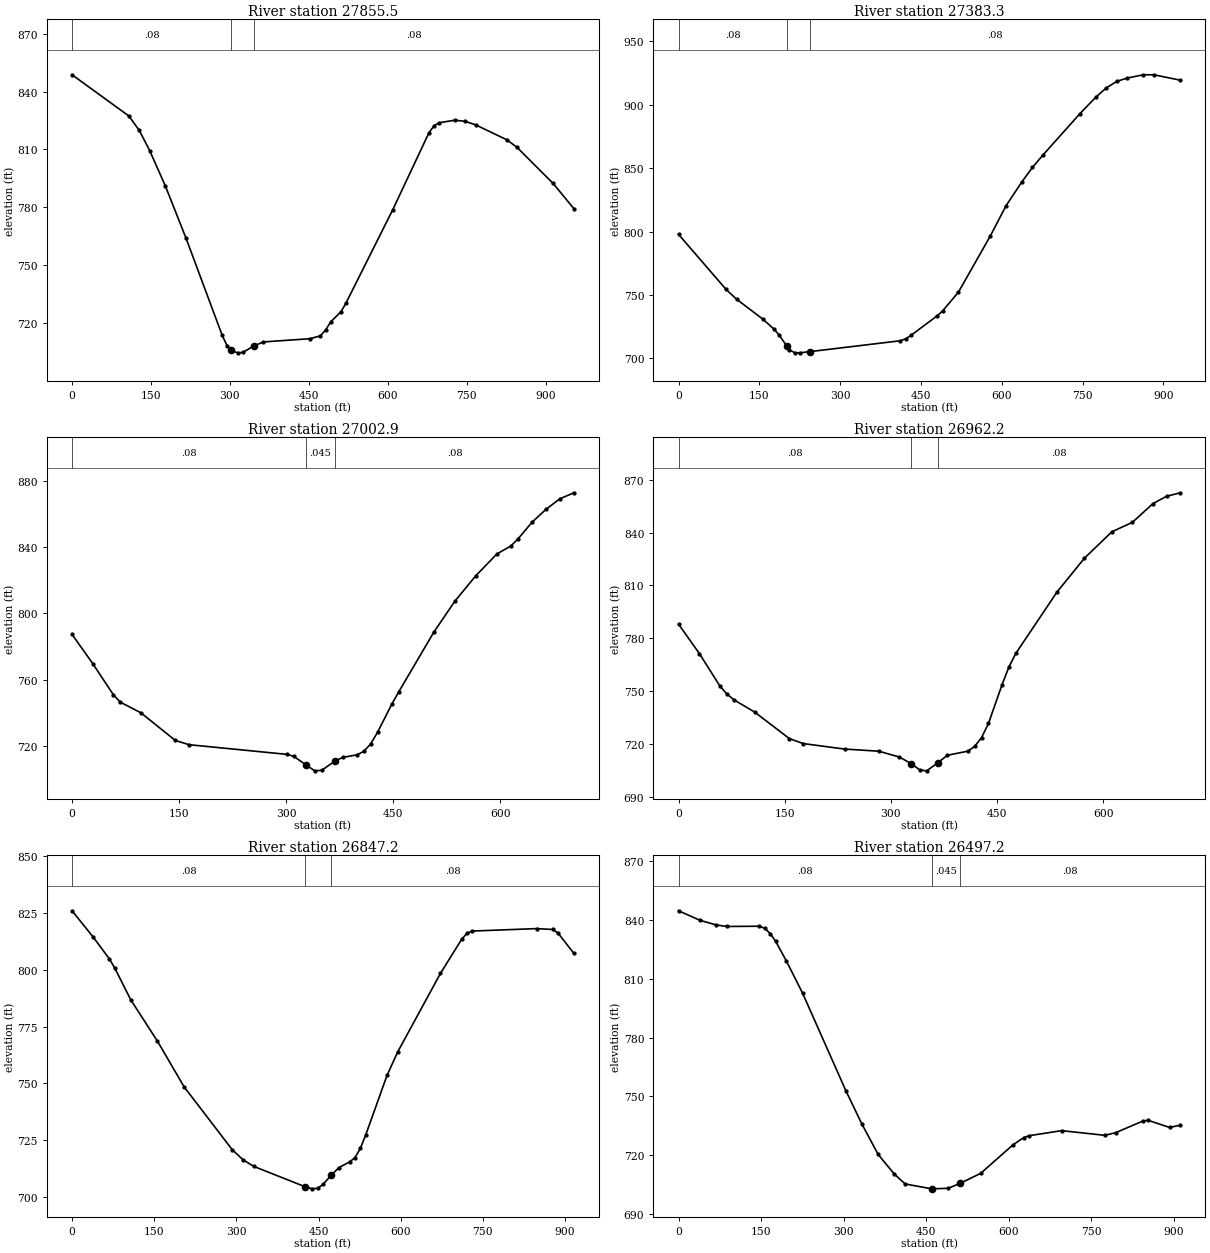
Type RM Length L Ch R = 1 ,27855.5 ,461.4,472.2,483
XS GIS Cut Line= 2
     1831235.849      610999.265     1830863.773      611877.281
#Sta/Elev= 30
       0  848.73   108.1  827.32   127.8  819.83   147.5  809.39     177  791.24
   216.3  764.16   285.1  713.72   294.9  707.95   302.5705.7468   314.6  704.49
   324.4  704.68   344.9707.9914   363.7  710.15   452.2  711.83   471.9  713.31
   481.7  716.29   491.6  720.55   511.2  725.86     521  730.56   609.5  778.75
   678.3   818.7   688.2  822.36     698  823.87   727.5  825.18   747.2  824.58
   766.8  822.78   825.8  815.06   845.5  811.12   914.3  792.34   953.6  779.29
#Mann= 3 , 0 , 0
       0     .08       0   302.5    .045       0   344.9     .08       0
Bank Sta=302.5,344.9
XS Rating Curve= 0 ,0
Exp/Cntr=0.3,0.1

Type RM Length L Ch R = 1 ,27383.3 ,368.4,380.4,392.5
XS GIS Cut Line= 2
     1830891.457      610931.476     1830165.213      611514.947
#Sta/Elev= 30
       0  797.81    88.3  754.34   107.9   746.6   156.9  730.82   176.5  723.35
   186.3  718.69   201.5709.3696   205.9  706.77   215.7  704.44   225.2  704.36
   244.4705.3452   411.9  713.89   421.7  715.41   431.5  718.14   480.5  733.65
   490.3   737.4   519.7  752.27   578.6  796.35     608  820.34   637.4  839.22
     657  850.54   676.6  860.39   745.3  893.05   774.7  906.01   794.3  913.37
   813.9  918.54   833.5  921.13     863  923.67   882.6  923.66   931.6   919.4
#Mann= 3 , 0 , 0
       0     .08       0   201.5    .045       0   244.4     .08       0
Bank Sta=201.5,244.4
XS Rating Curve= 0 ,0
Exp/Cntr=0.3,0.1

Type RM Length L Ch R = 1 ,27002.9 ,40.7,40.7,40.7
XS GIS Cut Line= 3
     1830832.311      610770.942     1830639.419      610770.942
     1830134.308      610844.009
#Sta/Elev= 30
       0  787.35    28.9  769.76    57.9  750.87    67.5  746.41    96.4  739.97
   144.7  723.25     164  720.66   300.8  714.84   310.7  713.63   327.4708.5808
   340.1  704.86   349.9  705.19   368.6710.8108   379.4     713     399   714.5
   408.8  716.59   418.6  721.17   428.4  728.38   448.1  745.16   457.9  752.65
     507  788.69   536.4  807.36   565.8   822.8   595.3  835.95   614.9   840.8
   624.7  844.96   644.4  855.04     664   862.9   683.6  869.33   703.3  872.99
#Mann= 3 , 0 , 0
       0     .08       0   327.4    .045       0   368.6     .08       0
Bank Sta=327.4,368.6
XS Rating Curve= 0 ,0
Exp/Cntr=0.3,0.1

Type RM Length L Ch R = 1 ,26962.2 ,112.6,115,117.4
XS GIS Cut Line= 3
     1830832.311      610730.942     1830636.541      610730.942
     1830128.581      610804.421
#Sta/Elev= 30
       0  788.02    29.4  771.33    58.7  752.69    68.5  748.24    78.3  744.99
   107.7     738   156.6  722.96   176.2  720.13   234.5  717.02   282.9  715.79
     312  712.49   328.4708.7958     341  705.13   350.7  704.63   366.4709.2253
   379.8  713.46   408.8  715.82   418.5  718.57   428.2  723.55   437.9  731.55
   457.2  753.69   466.9   763.8   476.6   771.4   534.7  806.26   573.4  825.47
   612.2  840.52   641.2  845.86   670.3  856.54   689.6  860.72     709   862.7
#Mann= 3 , 0 , 0
       0     .08       0   328.4    .045       0   366.4     .08       0
Bank Sta=328.4,366.4
XS Rating Curve= 0 ,0
Exp/Cntr=0.3,0.1

Type RM Length L Ch R = 1 ,26847.2 ,358.9,350,341.1
XS GIS Cut Line= 2
     1830932.393       610620.56     1830016.804       610657.46
#Sta/Elev= 30
       0  825.88      39   814.2    68.2  804.71      78  800.69   107.2  786.76
     156  768.56   204.7   748.5   292.4  720.94   311.9  716.55   331.4  713.62
     425 704.692   438.7  703.72   448.4     704   458.2  705.66   472.9709.6263
   487.4  713.08   506.9  715.57   516.7  717.47   526.4  721.46   536.2  727.38
   575.1  753.54   594.6  763.86   672.6  798.33   711.6  813.42   721.4  816.06
   731.1  816.97   848.1  818.05   877.3  817.67   887.1  816.17   916.3  807.18
#Mann= 3 , 0 , 0
       0     .08       0     425    .045       0   472.9     .08       0
Bank Sta=425,472.9
XS Rating Curve= 0 ,0
Exp/Cntr=0.3,0.1

Type RM Length L Ch R = 1 ,26497.2 ,475.5,479,482.5
XS GIS Cut Line= 2
     1830833.839      610108.285     1830005.788      610491.517
#Sta/Elev= 30
       0  844.68    39.2  839.81    68.7  837.45    88.3  836.68   147.2   836.8
     157  835.67   166.8  833.04   176.6   829.1   196.2  819.02   225.7  802.59
   304.1  753.02   333.6  735.82     363  720.42   392.4  710.41   412.1  705.38
   460.3702.9106   461.1   702.9   490.6  703.19   512.3705.7493   549.4   710.8
   608.3  725.38   627.9  729.05   637.7  730.01   696.6  732.57   775.1  730.19
   794.7  731.52   843.8   737.4   853.6  737.88   892.8  734.19   912.4  735.37
#Mann= 3 , 0 , 0
       0     .08       0   460.3    .045       0   512.3     .08       0
Bank Sta=460.3,512.3
XS Rating Curve= 0 ,0
Exp/Cntr=0.3,0.1

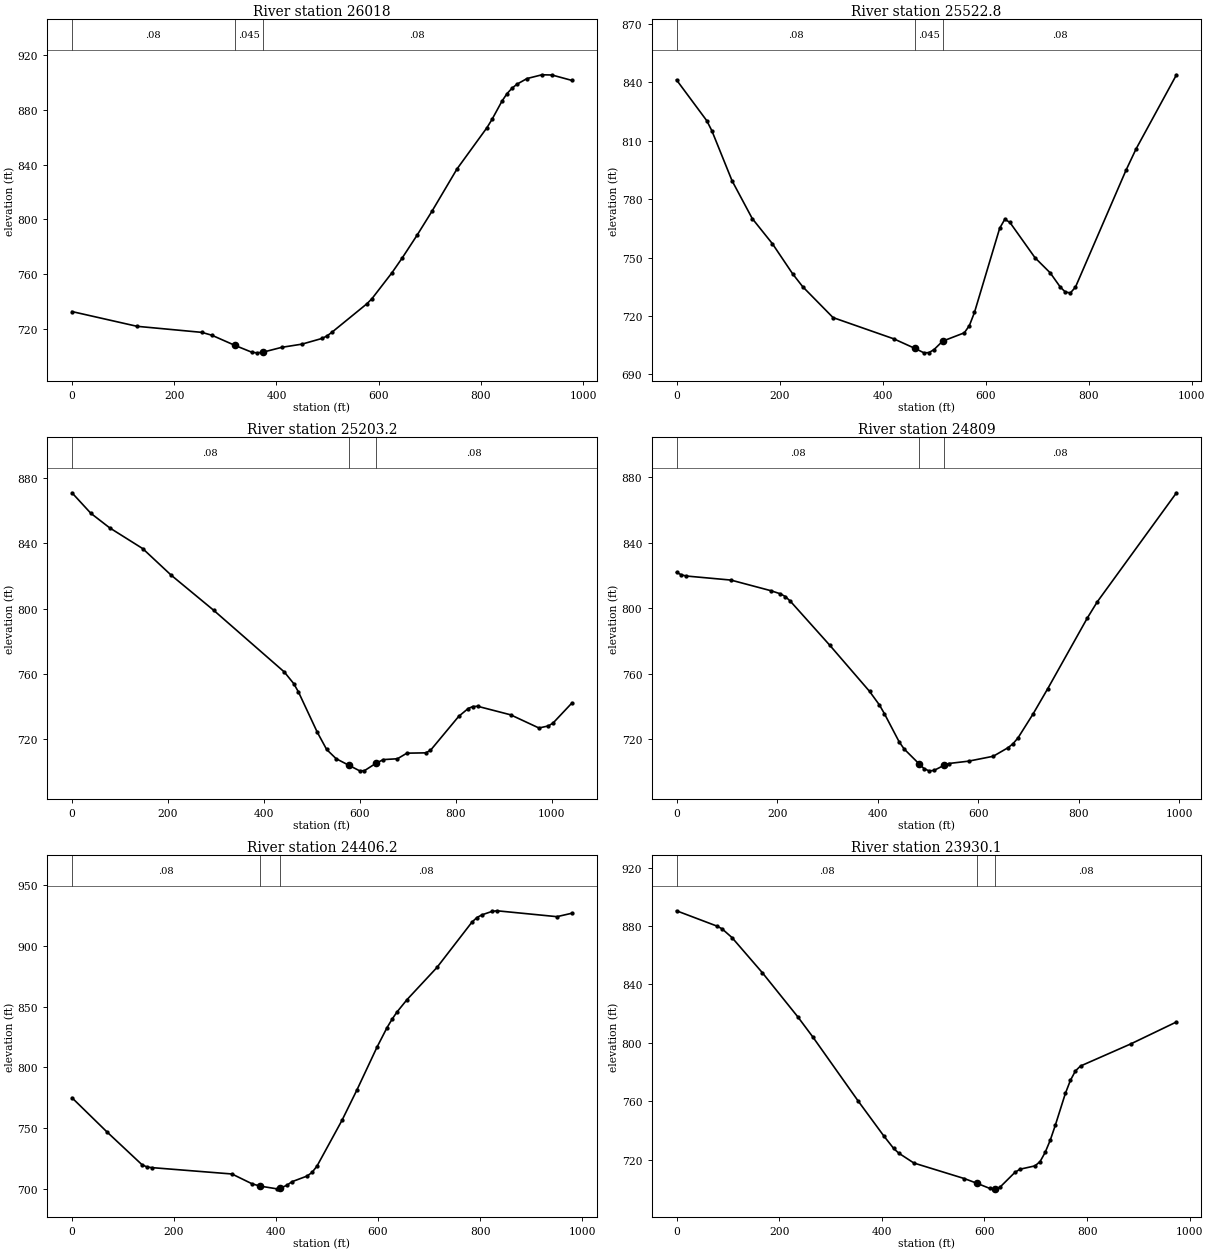
Type RM Length L Ch R = 1 ,26018   ,469.2,495.5,521.8
XS GIS Cut Line= 2
     1830559.661      609771.143     1829619.467      610040.586
#Sta/Elev= 30
       0  732.83   127.2  722.09   254.3  717.66   273.8  715.55   318.1708.2838
   352.1  703.15   361.9  702.75   372.9703.1702   410.8   706.8   449.9  709.09
     489  713.24   498.8  715.06   508.6  717.78     577  738.54   586.8  742.23
     626  761.16   645.5  771.64   674.8  788.33   704.2  805.95   753.1  836.74
   811.8  866.88   821.6  872.86   841.1  886.17   850.9  891.62   860.7   895.6
   870.5  898.54     890  902.64   919.4   905.4   938.9  905.24     978  901.28
#Mann= 3 , 0 , 0
       0     .08       0   318.1    .045       0   372.9     .08       0
Bank Sta=318.1,372.9
XS Rating Curve= 0 ,0
Exp/Cntr=0.3,0.1

Type RM Length L Ch R = 1 ,25522.8 ,337.3,319.4,301.4
XS GIS Cut Line= 2
      1830775.11      609926.438     1830158.369      609177.043
#Sta/Elev= 30
       0  841.29    58.8   820.3    68.6  815.17   107.8  789.47     147  770.04
   186.3  757.04   225.5  741.61   245.1  734.96   303.9  719.12   421.6  708.22
   463.2703.2416   480.4     701   490.2  701.13     500  702.69   516.6706.9957
   558.8   711.3   568.6  715.05   578.4  721.74   627.4  765.05   637.2  769.59
     647  768.12     696  749.87   725.5  742.11   745.1  734.79   754.9  732.25
   764.7   731.8   774.5  734.78   872.5  794.78   892.1  805.78   970.6  843.92
#Mann= 3 , 0 , 0
       0     .08       0   463.2    .045       0   516.6     .08       0
Bank Sta=463.2,516.6
XS Rating Curve= 0 ,0
Exp/Cntr=0.3,0.1

Type RM Length L Ch R = 1 ,25203.2 ,398.3,394.1,389.9
XS GIS Cut Line= 2
      1831329.55      609478.376     1830302.169      609305.497
#Sta/Elev= 30
       0  870.96    39.3  858.41    78.6  849.49   147.4   836.8   206.4  820.62
   294.9  799.15   442.3  761.34   461.9  754.25   471.8  749.15   511.1  724.46
   530.7  713.87   550.4  708.25   576.3704.3094   599.5  700.81   609.4  700.91
   632.8705.3094   648.7  707.69   678.2   708.2   697.8  711.62   737.1  711.82
     747  713.35   805.9  734.16   825.6  738.95   835.4  740.17   845.2  740.32
     914  735.09     973  727.03   992.7  728.29  1002.5  730.08  1041.8  742.34
#Mann= 3 , 0 , 0
       0     .08       0   576.3    .045       0   632.8     .08       0
Bank Sta=576.3,632.8
XS Rating Curve= 0 ,0
Exp/Cntr=0.3,0.1

Type RM Length L Ch R = 1 ,24809   ,384.8,402.8,420.9
XS GIS Cut Line= 2
     1831166.884      608974.079     1830178.822      609082.072
#Sta/Elev= 30
       0  821.99     9.8  820.44    19.7  819.72   108.2  817.25     187  810.81
   206.7  808.84   216.5  807.16   226.3  804.35   305.1   777.3   383.8  749.26
   403.5  740.92   413.3  735.65   442.8  718.35   452.7  714.01   482.2     705
     492  702.12   501.9  700.71   511.7  700.92   531.4  704.02   541.3  705.19
   580.6  706.62   629.8  709.62   659.4   714.9   669.2  717.32     679  720.87
   708.6  735.31   738.1  750.92   816.8   794.1   836.5  803.94     994  870.58
#Mann= 3 , 0 , 0
       0     .08       0   482.2    .045       0   531.4     .08       0
Bank Sta=482.2,531.4
XS Rating Curve= 0 ,0
Exp/Cntr=0.3,0.1

Type RM Length L Ch R = 1 ,24406.2 ,470.2,476.1,482.1
XS GIS Cut Line= 2
     1830930.226      608912.814     1830187.085      608273.764
#Sta/Elev= 30
       0  774.85    68.6  746.71   137.2  719.74     147  717.85   156.8  717.31
   313.6  712.07   352.8  704.03   368.6702.0934   401.8  699.84   408.2 700.369
   421.4  702.82   431.2  705.71   460.7  710.34   470.5  713.31   480.3  718.57
   529.3  756.25   558.7  781.37   597.9  816.48   617.5  832.52   627.3  839.38
   637.1  845.46   656.7  855.62   715.5  882.16   784.1  919.49   793.9  923.29
   803.7  925.48   823.3  928.31   833.1  928.83   950.7  923.98   980.1  926.82
#Mann= 3 , 0 , 0
       0     .08       0   368.6    .045       0   408.2     .08       0
Bank Sta=368.6,408.2
XS Rating Curve= 0 ,0
Exp/Cntr=0.3,0.1

Type RM Length L Ch R = 1 ,23930.1 ,350.9,347,343.1
XS GIS Cut Line= 2
     1831405.651      608952.149     1830859.062      608145.774
#Sta/Elev= 30
       0  890.47    78.7  879.99    88.6  878.15   108.2  872.09   167.3  848.02
   236.2  817.86   265.7  803.97   354.2  759.99   403.4  736.43   423.1  727.62
     433   724.4   462.5  717.62   560.9  706.96   585.4703.7294   610.1  700.26
   619.9  699.93   629.8  700.89   659.3  711.17   669.1  713.36   698.6  715.67
   708.5  718.65   718.3  724.88   728.2  733.22     738  743.38   757.7   765.3
   767.5  774.25   777.4  780.76   787.2  784.09   885.6  799.31   974.2  814.29
#Mann= 3 , 0 , 0
       0     .08       0   585.4    .045       0   619.9     .08       0
Bank Sta=585.4,619.9
XS Rating Curve= 0 ,0
Exp/Cntr=0.3,0.1

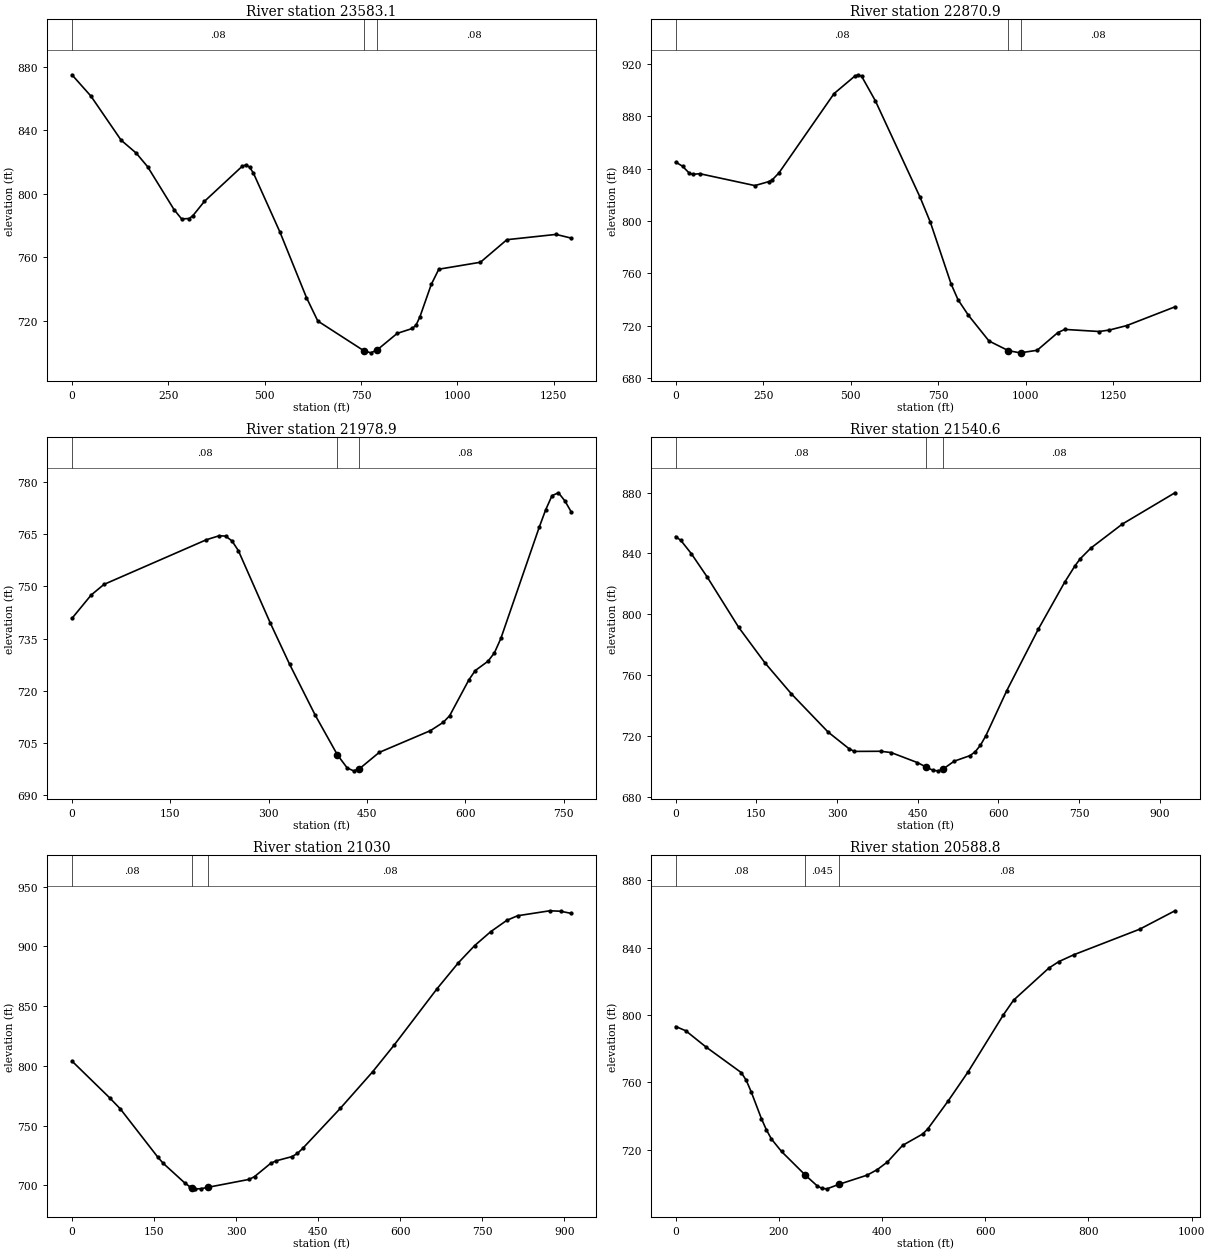
Type RM Length L Ch R = 1 ,23583.1 ,741.1,712.1,679.5
XS GIS Cut Line= 2
     1831905.929      608835.856     1831004.326      607905.502
#Sta/Elev= 30
       0  875.02    49.1  861.63   127.6  833.83   166.8  825.68   196.3  817.13
     265  790.08   284.6  784.23   304.3  784.48   314.1  786.35   343.5  795.22
   441.7  817.36   451.5  818.26   461.3  816.76   471.1  812.98   539.8  775.92
   608.5  734.73     638  719.91   756.6701.3328   775.4  699.88   792.3701.7811
   844.1  712.14   883.3  715.23   893.1  717.44     903  722.59   932.4  742.96
     952  752.56    1060  756.94  1128.7  771.15  1256.3  774.48  1295.6  772.13
#Mann= 3 , 0 , 0
       0     .08       0   756.6    .045       0   792.3     .08       0
Bank Sta=756.6,792.3
XS Rating Curve= 0 ,0
Exp/Cntr=0.3,0.1

Type RM Length L Ch R = 1 ,22870.9 ,918.7,892.3,869.5
XS GIS Cut Line= 2
     1832556.633      607301.432     1831245.317      607861.401
#Sta/Elev= 30
       0  845.14    19.7  841.94    39.3  836.56    49.2  835.75    68.8  836.24
   226.2  827.15   265.5  830.14   275.3  831.37     295  836.85   452.4  897.52
   511.4  910.84   521.2  911.91     531  910.82   570.4  891.97   698.2  818.14
   727.7  798.91   786.7  751.88   806.4  739.84   835.9     728   894.9  708.25
   950.2700.8831   983.4   699.2   984.9699.2337  1032.5  701.16  1091.5   714.7
  1111.2  717.12  1209.5  715.52    1239  716.66  1288.2  720.05  1425.9  734.38
#Mann= 3 , 0 , 0
       0     .08       0   950.2    .045       0   984.9     .08       0
Bank Sta=950.2,984.9
XS Rating Curve= 0 ,0
Exp/Cntr=0.3,0.1

Type RM Length L Ch R = 1 ,21978.9 ,429.4,437.9,446.4
XS GIS Cut Line= 2
     1830948.058      607001.484     1830983.304       607761.98
#Sta/Elev= 30
       0  740.81    29.3  747.54    48.8  750.59     205  763.45   224.5   764.6
   234.2   764.5     244  763.12   253.8   760.3   302.6  739.42   331.8  727.64
   370.9  712.97   404.9701.4951   419.7  697.76   429.5  696.93   437.8697.4434
   468.5  702.23   546.6   708.5   566.1  710.88   575.9  712.79   605.2   723.1
   614.9  725.79   634.4  728.48   644.2   730.9     654  735.04   712.5  767.05
   722.3  772.05     732  776.14   741.8  776.97   751.6  774.64   761.3  771.47
#Mann= 3 , 0 , 0
       0     .08       0   404.9    .045       0   437.8     .08       0
Bank Sta=404.9,437.8
XS Rating Curve= 0 ,0
Exp/Cntr=0.3,0.1

Type RM Length L Ch R = 1 ,21540.6 ,510.3,510.6,510.9
XS GIS Cut Line= 2
      1830694.31      606995.215     1830391.654      607872.687
#Sta/Elev= 30
       0  851.09     9.8  848.49    29.3  839.77    58.6   824.5   117.2  791.36
   166.1  767.95     215  747.67   283.4  722.49   322.4  711.52   332.2  709.75
     381  709.84   400.6     709   449.4  702.41   465.5699.5193   478.8  697.23
   488.5  696.97   496.8698.0541   517.8  703.32   547.2  706.97   556.9  709.52
   566.7  713.87   576.5  719.92   615.5  749.68   674.2  790.16     723  820.93
   742.6  831.95   752.3  836.53   771.9  843.51   830.5  859.32   928.2  879.88
#Mann= 3 , 0 , 0
       0     .08       0   465.5    .045       0   496.8     .08       0
Bank Sta=465.5,496.8
XS Rating Curve= 0 ,0
Exp/Cntr=0.3,0.1

Type RM Length L Ch R = 1 ,21030   ,438.7,441.3,443.8
XS GIS Cut Line= 2
     1830194.224      606946.374     1829884.355      607804.485
#Sta/Elev= 30
       0  804.05    68.7  773.37    88.3  764.06     157  723.55   166.8  718.42
     206  702.07   215.8  698.72     219698.1812   225.6  697.07   235.4  697.16
   248.4  698.34   323.7  704.98   333.6  707.31     363  718.36   372.8  720.48
   402.2  724.07     412  726.72   421.8  730.99   490.5  764.53   549.4  795.04
   588.6  817.35   667.1  864.59   706.3  886.45   735.8   900.7   765.2  912.37
   794.6  921.85   814.2  925.69   873.1  929.86   892.7  929.49   912.3  927.67
#Mann= 3 , 0 , 0
       0     .08       0     219    .045       0   248.4     .08       0
Bank Sta=219,248.4
XS Rating Curve= 0 ,0
Exp/Cntr=0.3,0.1

Type RM Length L Ch R = 1 ,20588.8 ,487.8,512,536.2
XS GIS Cut Line= 2
     1829831.913      606751.908     1829403.262      607619.367
#Sta/Elev= 30
       0   793.2    19.6  790.68    58.6  781.09   127.1  765.86   136.8  761.29
   146.6  754.26   166.2  738.52   175.9  731.84   185.7  726.38   205.2     719
   251.5704.9133   273.7  698.76   283.4  697.06   293.2  696.83     316699.4523
   371.4  704.99   390.9  708.28   410.5  712.79   439.8  722.62   478.9  729.41
   488.7  732.43   527.8  748.86   566.9  766.34   635.3   800.2   654.8  808.81
   723.2  827.88   742.8  831.76   772.1  835.85   899.2  850.95   967.6   861.9
#Mann= 3 , 0 , 0
       0     .08       0   251.5    .045       0     316     .08       0
Bank Sta=251.5,316
XS Rating Curve= 0 ,0
Exp/Cntr=0.3,0.1

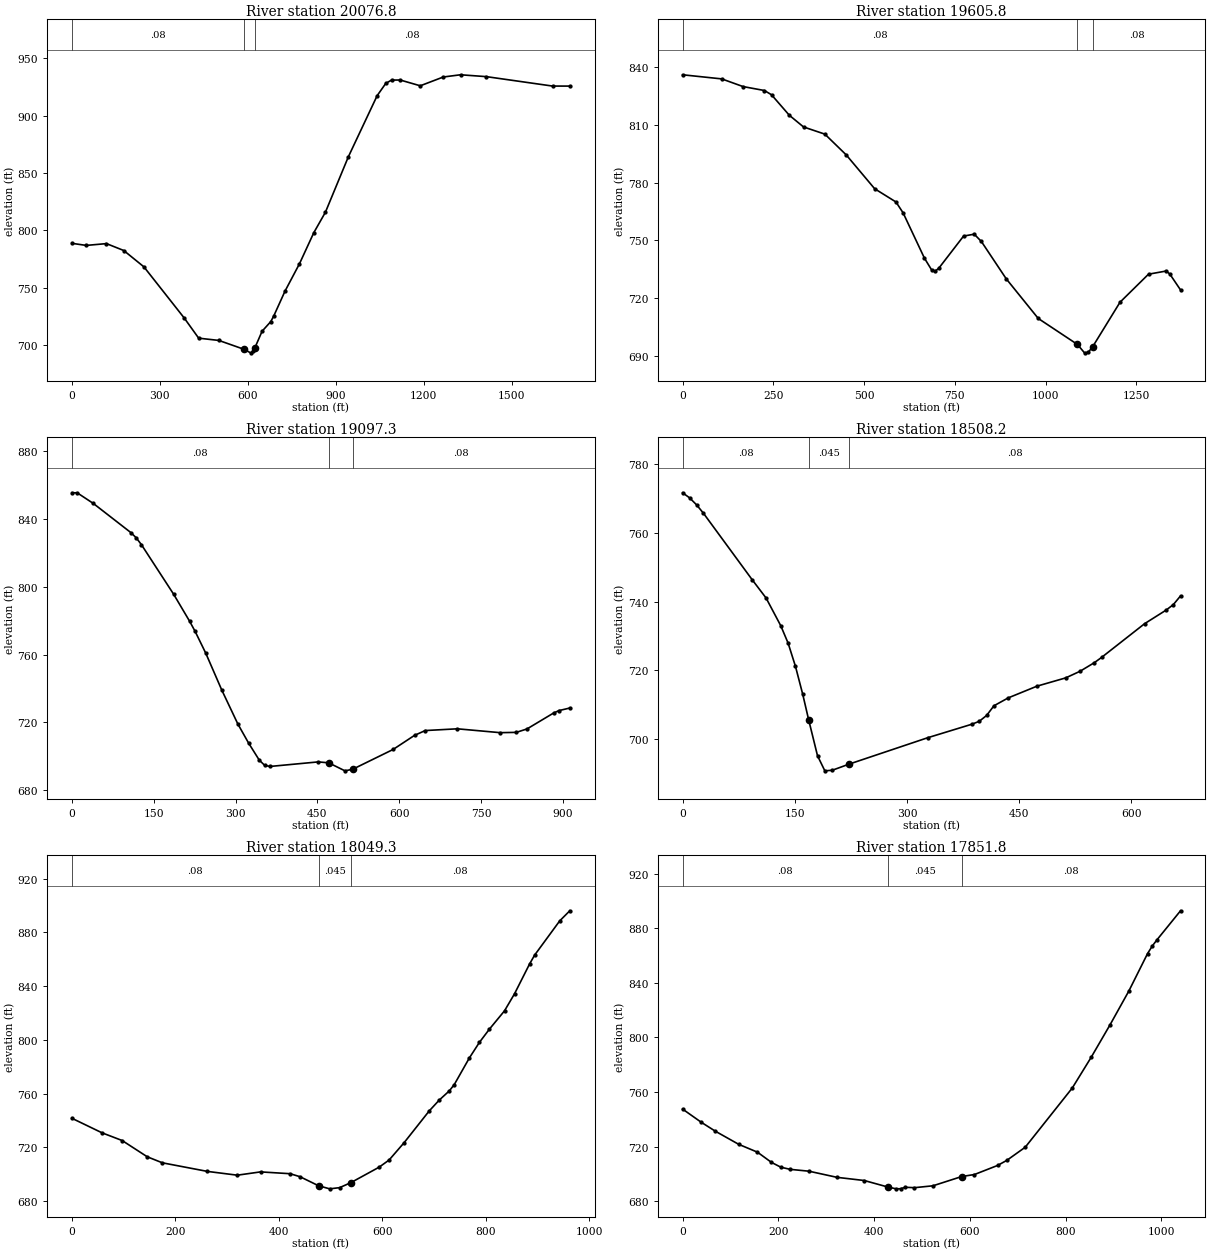
Type RM Length L Ch R = 1 ,20076.8 ,462.7,470.6,478.4
XS GIS Cut Line= 3
     1829954.489      606627.175     1829228.308      606665.579
     1828521.124      607330.564
#Sta/Elev= 30
       0  788.69    49.1  786.87   117.9  788.44   176.9  782.43   245.7  768.17
   383.2  723.55   432.4  706.01   501.2  704.04   587.6696.2604   609.3  693.22
   619.1  694.91   623.2697.0855   648.6  712.04   678.1  720.41   687.9  725.06
   727.2  747.23   776.2  770.92   825.2  798.07   864.5  815.76   942.9  864.18
    1041  917.41  1070.4  928.11    1090  930.99  1119.4  931.07    1188  926.02
  1266.5  933.68  1325.3  935.62  1413.6  933.99  1639.1  925.78  1697.9  925.76
#Mann= 3 , 0 , 0
       0     .08       0   587.6    .045       0   623.2     .08       0
Bank Sta=587.6,623.2
XS Rating Curve= 0 ,0
Exp/Cntr=0.3,0.1

Type RM Length L Ch R = 1 ,19605.8 ,546.2,508.5,468.5
XS GIS Cut Line= 2
     1830629.313      606564.745     1829315.876      606169.551
#Sta/Elev= 30
       0  835.76   107.8  833.63   166.6  829.65   225.3  827.62   244.9  825.42
   293.9  814.82   333.1  808.76   391.9  805.04   450.7   794.3     529  776.79
   587.8  769.92   607.4   764.3   666.2  740.84   685.8  734.82   695.6  734.13
   705.4  735.56     774  752.28   803.4  753.26     823  749.48   891.5  730.16
   979.7  709.64  1087.5  696.21  1107.1  691.85  1116.9  692.04  1129.2694.8912
    1205  718.06  1283.4  732.55  1332.4   734.2  1342.2   732.6  1371.6  724.42
#Mann= 3 , 0 , 0
       0     .08       0  1087.5    .045       0  1129.2     .08       0
Bank Sta=1087.5,1129.2
XS Rating Curve= 0 ,0
Exp/Cntr=0.3,0.1

Type RM Length L Ch R = 1 ,19097.3 ,615.9,589.1,564.4
XS GIS Cut Line= 2
     1829745.063      605296.548     1829428.911      606152.893
#Sta/Elev= 30
       0  855.46     9.8  855.43    39.3  849.17     108  832.01   117.8  828.95
   127.6   824.8   186.5  795.64   215.9  779.63   225.8  773.77   245.4  760.85
   274.8  739.07   304.3  719.02   323.9  707.82   343.5  697.74   353.4  694.65
   363.2  693.99   451.5  696.67   470.8696.1368   500.6   691.4   514.7692.3223
   588.9  704.01   628.2  712.34   647.8  715.17   706.7   716.2   785.2  713.92
   814.7   714.1   834.3  716.11   883.4  725.57   893.2  726.97   912.8  728.46
#Mann= 3 , 0 , 0
       0     .08       0   470.8    .045       0   514.7     .08       0
Bank Sta=470.8,514.7
XS Rating Curve= 0 ,0
Exp/Cntr=0.3,0.1

Type RM Length L Ch R = 1 ,18508.2 ,447.7,459,470.3
XS GIS Cut Line= 4
     1829099.498      605776.344     1829092.074       605887.69
      1829344.46      606058.421      1829247.96      606288.537
#Sta/Elev= 30
       0  771.75     9.3  770.28    18.6  768.26    27.9  765.78      93  746.43
   111.6   741.1   131.2  733.05   141.1  727.94   150.9   721.2   160.7  712.99
   168.6705.5768   180.4  695.14   190.2  690.75   200.1  690.92   222.6692.7067
   327.8   700.4   386.8  704.33   396.6  705.17   406.5  706.88   416.3   709.7
   435.5  712.01   473.9  715.42   512.3  717.83   531.5  719.76   550.7  722.28
   560.3   723.8   617.8  733.62   646.6  737.58   656.2  739.18   665.8   741.7
#Mann= 3 , 0 , 0
       0     .08       0   168.6    .045       0   222.6     .08       0
Bank Sta=168.6,222.6
XS Rating Curve= 0 ,0
Exp/Cntr=0.3,0.1

Type RM Length L Ch R = 1 ,18049.3 ,189.1,197.5,114.7
XS GIS Cut Line= 6
     1829021.117      605903.137     1828938.757      606068.269
     1828803.922      606060.915     1828800.305      606066.598
     1828897.615      606325.788     1828812.444       606674.34
#Sta/Elev= 30
       0  741.64    58.3   730.8    97.1  725.08   145.7  712.95   174.8  708.48
   261.7  702.09   319.6  699.26   364.5  701.72   421.8  700.36   440.9  698.11
   476.6691.3969   498.1   689.1   517.2  689.98   538.7693.6475   593.6  705.22
   612.9  710.56     642  723.51   690.4   747.1   709.8  755.19   729.2  762.02
   738.9  766.77     768  786.58   787.4  798.15   806.8  808.04   835.9  821.64
   855.3  834.37   884.4  856.58   894.1  863.13   942.6  888.63     962  896.12
#Mann= 3 , 0 , 0
       0     .08       0   476.6    .045       0   538.7     .08       0
Bank Sta=476.6,538.7
XS Rating Curve= 0 ,0
Exp/Cntr=0.3,0.1

Type RM Length L Ch R = 1 ,17851.8 ,183.9,219.6,346.4
XS GIS Cut Line= 6
     1829021.117      605853.737     1828935.775      605984.794
     1828769.786       605975.74     1828719.224      606108.974
     1828829.822      606333.868     1828744.565      606646.959
#Sta/Elev= 30
       0  747.45    39.1  737.76    68.4  731.24   117.3   721.6   156.4  715.86
   185.7  708.36   205.3  704.83   224.8  703.27     264  701.91   322.6  697.41
   379.6  695.08   428.1690.3773   446.1  688.98   455.6  689.07   465.1  690.12
   484.4  689.83     523  691.21     583697.9923   609.7  699.48   657.9  706.11
   677.2  709.83   715.8   719.5   814.1  762.93   853.4  785.34   892.8  809.15
   932.1  833.93   971.4  861.51   981.2  867.02   991.1  871.61  1040.2  892.86
#Mann= 3 , 0 , 0
       0     .08       0   428.1    .045       0     583     .08       0
Bank Sta=428.1,583
XS Rating Curve= 0 ,0
Exp/Cntr=0.3,0.1

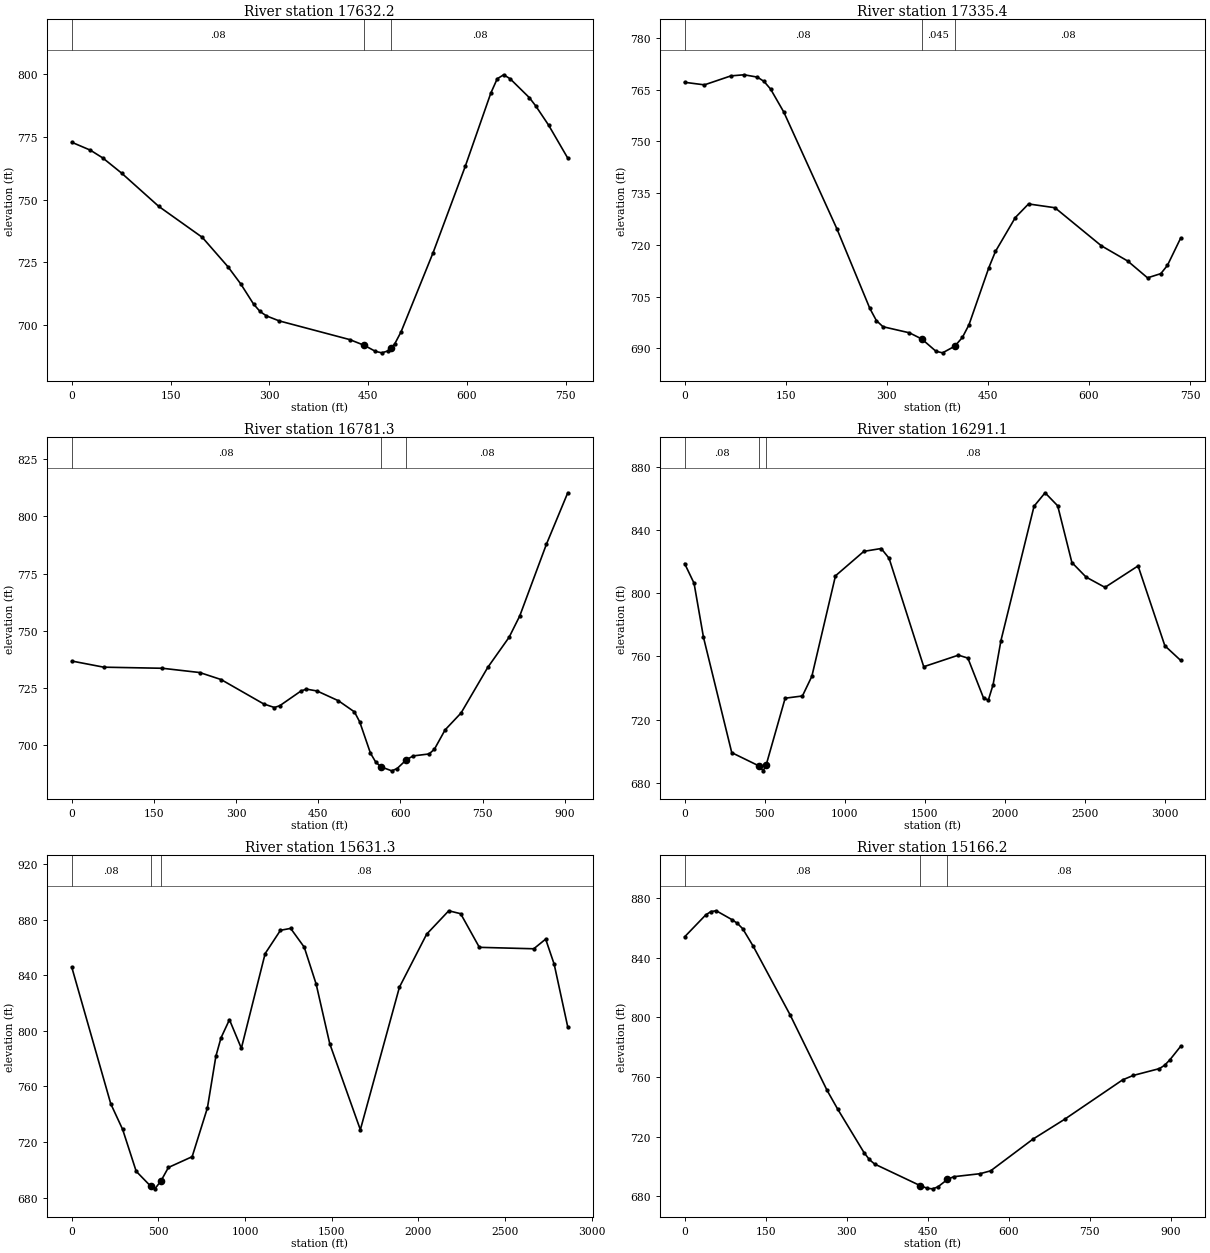
Type RM Length L Ch R = 1 ,17632.2 ,298.3,296.9,295.4
XS GIS Cut Line= 3
      1829030.34      605664.248     1828972.971      605853.923
     1828421.193      605912.162
#Sta/Elev= 30
       0  772.82    28.3  769.66    47.2  766.55    75.5  760.57   132.1  747.28
   198.2  734.95   237.1  723.26   256.6  716.39     276  708.39   285.8  705.45
   295.5  703.69     315  701.69     422  694.25   444.1691.9621     461  689.57
   470.7  688.98   480.4  689.77   484.8690.9957   490.2   692.5   499.9  697.33
   548.6   728.9   597.3  763.19   636.2  792.41   645.9   798.1   655.7  799.69
   665.4  798.12   694.6   790.6   704.3  787.31   723.8  779.68     753  766.49
#Mann= 3 , 0 , 0
       0     .08       0   444.1    .045       0   484.8     .08       0
Bank Sta=444.1,484.8
XS Rating Curve= 0 ,0
Exp/Cntr=0.3,0.1

Type RM Length L Ch R = 1 ,17335.4 ,553.5,554,554.6
XS GIS Cut Line= 2
     1829089.652      605520.537     1828364.244      605645.722
#Sta/Elev= 30
       0  767.12    29.4  766.38    68.7  768.98    88.3   769.3     108  768.62
   117.8  767.38   127.6  765.15   147.2  758.48   225.8  724.73   274.8  701.61
   284.6  698.04   294.4  696.27   333.7   694.5     352692.7071     373  689.16
   382.8   688.7   400.9 690.617   412.2  693.16     422  696.83   451.5   713.4
   461.3  718.09   490.8  727.92   510.4  731.86   549.6  730.76   618.4  719.74
   657.6  715.31     687  710.44   706.7  711.66   716.5  714.04   736.1  721.93
#Mann= 3 , 0 , 0
       0     .08       0     352    .045       0   400.9     .08       0
Bank Sta=352,400.9
XS Rating Curve= 0 ,0
Exp/Cntr=0.3,0.1

Type RM Length L Ch R = 1 ,16781.3 ,494.3,490.1,485.9
XS GIS Cut Line= 2
     1829149.281      604994.321     1828253.748      605128.758
#Sta/Elev= 30
       0  736.68    58.4  733.99   165.5  733.51   233.7  731.64   272.6  728.57
   350.5  717.88     370  716.33   379.8  717.12   418.7  723.59   428.4  724.38
   447.9  723.56   486.9  719.28   516.1  714.41   525.8  709.99   545.3  696.35
     555  692.41   564.5690.3452   584.2  688.59     594  689.59   610.5693.3463
   623.2  695.12   652.4  695.99   662.1  698.06   681.6  706.52   710.8  713.94
   759.5  733.89   798.5   747.1   817.9  756.42   866.6  787.83   905.6  810.37
#Mann= 3 , 0 , 0
       0     .08       0   564.5    .045       0   610.5     .08       0
Bank Sta=564.5,610.5
XS Rating Curve= 0 ,0
Exp/Cntr=0.3,0.1

Type RM Length L Ch R = 1 ,16291.1 ,649.7,659.9,670.1
XS GIS Cut Line= 3
     1828943.878      604455.492     1828188.626      604701.365
     1826873.946      606591.343
#Sta/Elev= 30
       0  818.73    58.8  806.32   117.7  772.09   294.2  699.09   464.3690.6786
   490.3  687.58   508.5691.0843   627.6  733.54   735.4  734.95   794.3  747.39
   941.8  810.98  1118.9  826.45  1227.2  828.26  1276.4  822.08  1492.8  753.46
  1709.3  760.78  1768.3  758.92  1866.7  733.51  1896.2  732.37  1925.7  742.06
  1974.9  770.05  2181.5  855.03  2250.4  863.52  2329.1  855.27  2417.7  819.39
  2506.2  810.19  2624.3  803.67  2830.9  817.25  2998.1  766.72  3096.5  757.48
#Mann= 3 , 0 , 0
       0     .08       0   464.3    .045       0   508.5     .08       0
Bank Sta=464.3,508.5
XS Rating Curve= 0 ,0
Exp/Cntr=0.3,0.1

Type RM Length L Ch R = 1 ,15631.3 ,474.8,465.1,455.5
XS GIS Cut Line= 3
     1828853.801      604021.752     1827950.739      603909.596
      1826673.07       605386.09
#Sta/Elev= 30
       0  845.76     225  747.51   293.6  729.06   371.8  698.96   455.3688.2657
   479.4  686.35   513.9691.8541   557.7  701.72   694.7  709.47   782.8  744.57
   831.7  781.75   861.1   794.9     910  808.02   978.7  787.44    1116  855.56
  1204.4  872.31  1263.2  873.68  1341.7  860.16  1410.4  833.63  1488.9  790.73
  1665.5  728.85  1891.2  831.45  2048.2  869.53  2175.7  886.35  2244.4  884.24
  2352.3  860.06  2666.3  859.02    2735  865.97  2784.1  847.94  2862.6  802.75
#Mann= 3 , 0 , 0
       0     .08       0   455.3    .045       0   513.9     .08       0
Bank Sta=455.3,513.9
XS Rating Curve= 0 ,0
Exp/Cntr=0.3,0.1

Type RM Length L Ch R = 1 ,15166.2 ,544.2,537.9,531.6
XS GIS Cut Line= 2
     1828819.803      603364.427     1827944.455      603641.875
#Sta/Elev= 30
       0  853.99    39.1   868.7    48.8  870.97    58.6  871.47    87.9  865.47
    97.7  863.03   107.5  859.46     127  847.69   195.4   801.6   263.8     751
   283.3  738.51   332.1  709.33   341.9   704.7   351.7  701.64   436.4687.1157
   449.4  685.34   459.1     685   468.9  686.31   486.6691.3164   498.2  693.14
     547  695.15   566.6  697.08   644.7  718.28   703.4  731.61   810.8  758.05
   830.4  761.03   879.2  765.64     889  767.97   898.7  771.65   918.3  780.55
#Mann= 3 , 0 , 0
       0     .08       0   436.4    .045       0   486.6     .08       0
Bank Sta=436.4,486.6
XS Rating Curve= 0 ,0
Exp/Cntr=0.3,0.1