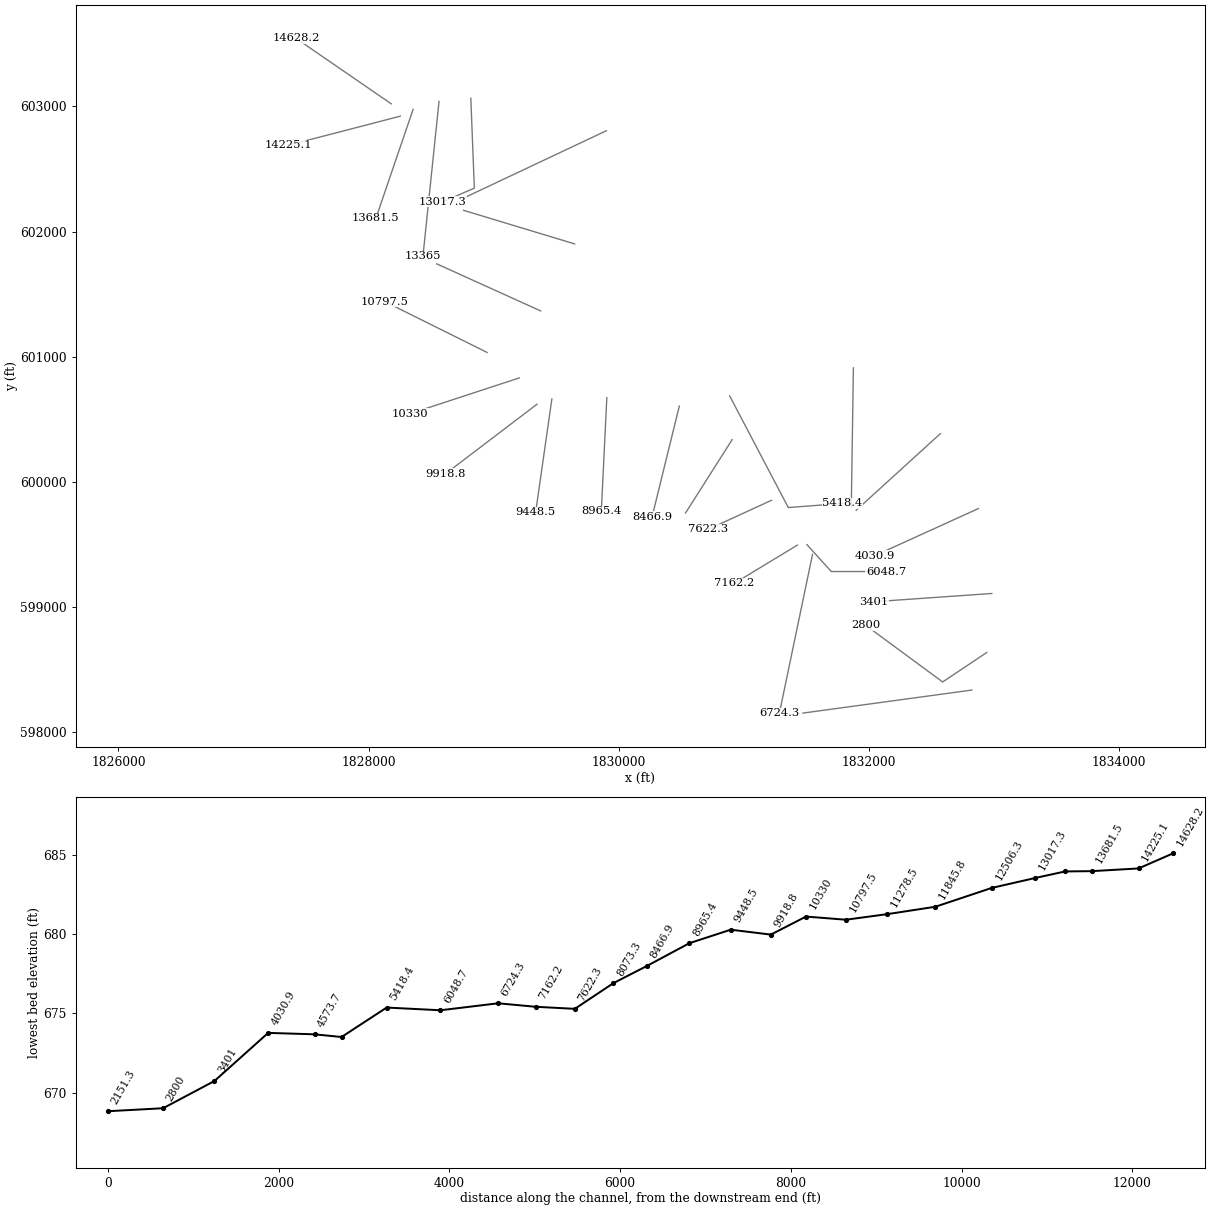
HEC-RAS study FlatFork.prj: FlatFork

--- FlatFork.g01 (geometry) --- (continued)

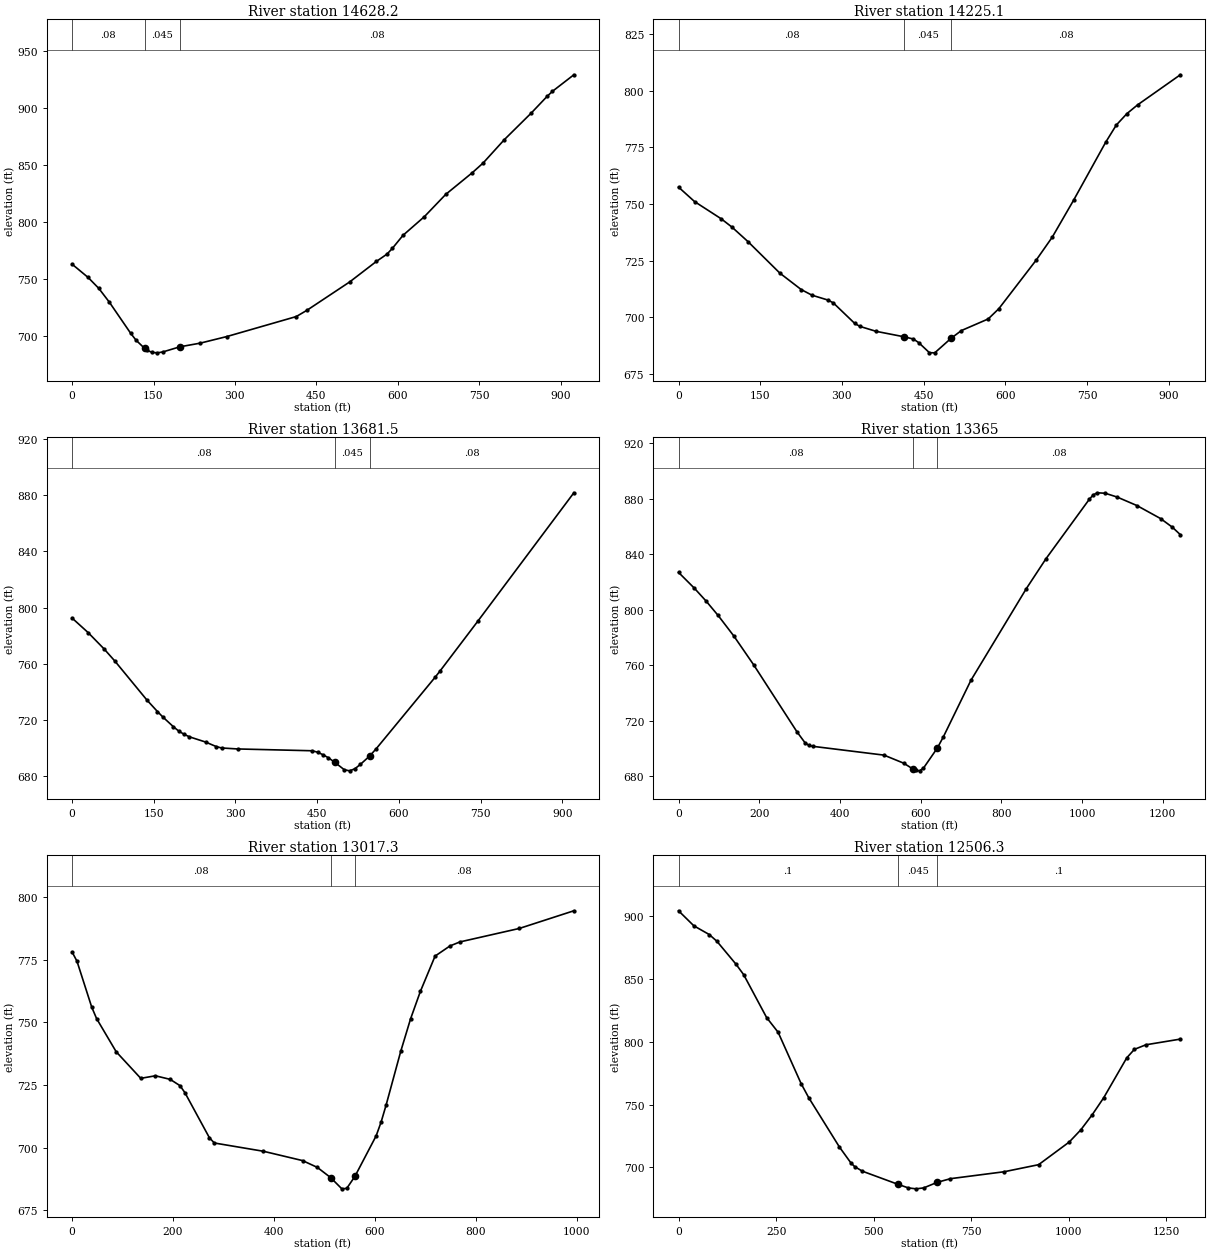
Type RM Length L Ch R = 1 ,14628.2 ,383.7,403.1,422.6
XS GIS Cut Line= 2
      1828181.92      603020.965     1827420.161      603544.392
#Sta/Elev= 30
       0  762.82    29.5   751.2    49.2  741.62    68.8  729.43   108.2  702.07
     118  696.11   133.7688.9911   137.7  687.48   147.5  685.47   157.3  685.11
   167.2   685.9   198.4  690.38     236   693.6   285.1  699.39     413  716.91
   432.6  722.39   511.3  747.23   560.4  765.17   580.1  771.64     590  776.68
   609.6   788.1     649  804.48   688.3  823.98   737.4  843.05   757.1  851.44
   796.4  872.03   845.6  895.16   875.1  909.91   884.9  914.32   924.3   928.8
#Mann= 3 , 0 , 0
       0     .08       0   133.7    .045       0   198.4     .08       0
Bank Sta=133.7,198.4
XS Rating Curve= 0 ,0
Exp/Cntr=0.3,0.1

Type RM Length L Ch R = 1 ,14225.1 ,521.5,543.6,565.6
XS GIS Cut Line= 2
     1828254.691      602922.678     1827363.002      602691.002
#Sta/Elev= 30
       0  757.46    29.4  751.07    78.4  743.44      98  739.79   127.4  733.38
   186.2  719.38   225.4  712.12     245  709.66   274.4   707.5   284.2  706.25
   323.4  697.19   333.2  695.84   362.6  693.68   414.5691.2357   431.2  690.27
     441  688.67   460.6  684.23   470.4  684.16   500.6690.6375   519.4  694.02
   568.5  699.14   588.1  703.69   656.7  725.19   686.1  735.31   725.3  751.65
   784.1  777.24   803.7   784.9   823.3  789.98   842.9  793.85   921.3  807.15
#Mann= 3 , 0 , 0
       0     .08       0   414.5    .045       0   500.6     .08       0
Bank Sta=414.5,500.6
XS Rating Curve= 0 ,0
Exp/Cntr=0.3,0.1

Type RM Length L Ch R = 1 ,13681.5 ,311.5,316.6,321.7
XS GIS Cut Line= 2
     1828356.384      602976.567     1828058.533      602104.748
#Sta/Elev= 30
       0  792.59    29.4  782.29    58.8  770.64    78.4   762.1   137.2  734.42
   156.8  726.13   166.6  722.29   186.2  715.28     196  712.22   205.8  709.94
   215.6  708.15     245  704.48   264.6  701.26   274.4  700.25   303.8  699.55
     441  698.26   450.8  697.23   460.6  695.45   470.4  693.33   482.5690.0067
   499.8  684.77   509.6  683.99   519.4   685.5   529.2  688.53   546.5694.5608
   558.7  699.84   666.5  750.48   676.3  755.31   744.9  790.33   921.3  881.64
#Mann= 3 , 0 , 0
       0     .08       0   482.5    .045       0   546.5     .08       0
Bank Sta=482.5,546.5
XS Rating Curve= 0 ,0
Exp/Cntr=0.3,0.1

Type RM Length L Ch R = 1 ,13365   ,344.3,347.6,350.8
XS GIS Cut Line= 2
     1828563.615      603039.911      1828435.19      601803.164
#Sta/Elev= 30
       0  827.06    39.2  815.66    68.5  806.31    97.9  796.07   137.1  781.16
     186  760.48   293.7     712   313.3  704.26   323.1  702.32   332.9  701.64
   509.1   695.3   558.1  689.47     580685.4306   587.4  684.23   597.2  683.97
     607  685.96   641.2 700.372     656  708.34   724.5  749.23   861.6  815.26
   910.5  836.91  1018.2  879.91    1028  883.03  1037.8  884.46  1057.4  884.11
  1086.8  881.38  1135.7  875.27  1194.4  865.88  1223.8   859.6  1243.4  854.25
#Mann= 3 , 0 , 0
       0     .08       0     580    .045       0   641.2     .08       0
Bank Sta=580,641.2
XS Rating Curve= 0 ,0
Exp/Cntr=0.3,0.1

Type RM Length L Ch R = 1 ,13017.3 ,543.9,511,472
XS GIS Cut Line= 3
     1828817.891       603066.28     1828846.141      602347.553
     1828593.709      602238.374
#Sta/Elev= 30
       0  778.12     9.7  774.44    38.9  756.12    48.6  751.52    87.5  738.26
   136.1  727.67   165.2  728.69   194.4  727.26   213.8  724.76   223.6  721.95
   272.2  703.93   281.9  701.86   379.1  698.56   456.8  694.83     486  692.12
   512.3 688.057   534.6  683.56   544.3  683.75   560.4688.5063   602.6  704.74
   612.4  710.24   622.1  716.88   651.2  738.41   670.7  751.39   690.1  762.34
   719.3  776.47   748.8  780.52   768.4  782.12   886.3  787.51   994.3  794.56
#Mann= 3 , 0 , 0
       0     .08       0   512.3    .045       0   560.4     .08       0
Bank Sta=512.3,560.4
XS Rating Curve= 0 ,0
Exp/Cntr=0.3,0.1

Type RM Length L Ch R = 1 ,12506.3 ,669.6,660.4,656.1
XS GIS Cut Line= 2
     1829901.515      602805.975     1828738.107      602257.463
#Sta/Elev= 30
       0  904.19    39.3  892.22    78.6  885.31    98.2  879.98   147.3  861.68
   166.9  853.38   225.8  819.21   255.3   807.5   314.2  766.67   333.8  755.41
   412.4   716.2   441.8  703.57   451.6  700.59   471.3  696.96   562.6686.5093
   589.1  683.67   608.8  682.93   628.4  683.68   662.9688.0976   697.1  691.02
   834.6  696.53   922.9  702.15  1001.5  720.19    1031  729.83  1060.4   741.9
  1089.9  755.46  1148.8  787.13  1168.4  793.91  1197.9  797.55  1286.2  802.08
#Mann= 3 , 0 , 0
       0      .1       0   562.6    .045       0   662.9      .1       0
Bank Sta=562.6,662.9
XS Rating Curve= 0 ,0
Exp/Cntr=0.3,0.1

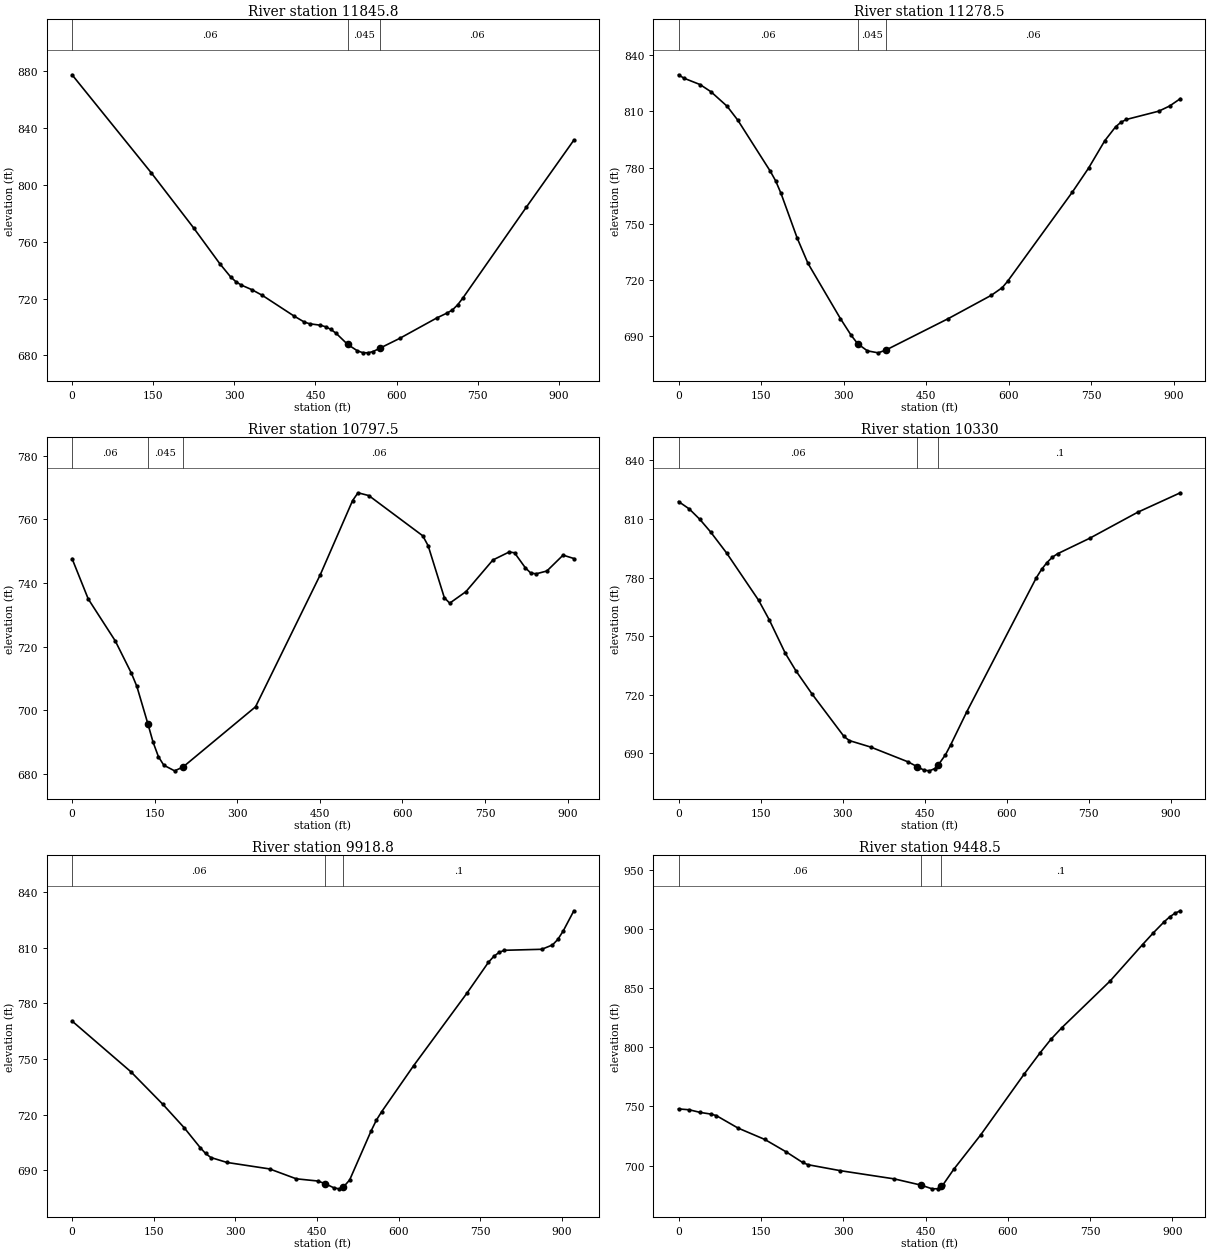
Type RM Length L Ch R = 1 ,11845.8 ,571.9,567.3,563.9
XS GIS Cut Line= 2
     1829647.907      601901.764     1828759.941       602169.99
#Sta/Elev= 30
       0  877.65   146.5  808.53   224.6  769.82   273.4   744.4   292.9  735.33
   302.7   731.9   312.4  729.56     332   726.3   351.5   722.3   410.1  707.72
   429.6  703.37   439.4  702.21   458.9  701.21   468.7  700.12   478.4  698.25
   488.2  695.48   509.2687.7568   527.3  683.19     537   681.9   546.8  681.74
   556.6  682.68   568.5 684.911   605.4  691.88   673.7  706.21   693.2  709.79
     703  711.92   712.8  715.56   722.6  720.46   839.7  784.34   927.6  831.61
#Mann= 3 , 0 , 0
       0     .06       0   509.2    .045       0   568.5     .06       0
Bank Sta=509.2,568.5
XS Rating Curve= 0 ,0
Exp/Cntr=0.3,0.1

Type RM Length L Ch R = 1 ,11278.5 ,481.9,481,480.2
XS GIS Cut Line= 2
     1829376.655      601366.062     1828545.461      601742.278
#Sta/Elev= 30
       0  829.54     9.8  827.72    39.2  824.32    58.9  820.51    88.3  812.77
   107.9  805.28   166.8  778.13   176.6  772.97   186.4  766.24   215.8  742.43
   235.4  728.95   294.3  699.55   313.9  690.61   325.9686.0867   343.4  682.33
     363  681.27   377.6682.8284   490.5  699.53     569     712   588.6  716.04
   598.4  719.44   716.2  767.04   745.6  779.79     775  794.37   794.6  801.76
   804.5  804.24   814.3  805.71   873.1  810.13   892.8  812.86   912.4   816.8
#Mann= 3 , 0 , 0
       0     .06       0   325.9    .045       0   377.6     .06       0
Bank Sta=325.9,377.6
XS Rating Curve= 0 ,0
Exp/Cntr=0.3,0.1

Type RM Length L Ch R = 1 ,10797.5 ,449.7,467.3,485
XS GIS Cut Line= 2
     1828948.053      601034.442     1828131.858      601439.746
#Sta/Elev= 30
       0  747.65    29.4  734.96    78.4  721.79   107.8   711.6   117.6  707.51
   137.7695.7034     147     690   156.8  685.38   166.6  682.69   186.2  680.92
   201.4682.1138   333.2  701.06   450.7  742.56   509.5  765.92   519.3  768.36
   538.9  767.48   636.9  754.83   646.7   751.7   676.1  735.35   685.9  733.65
   715.3  737.27   764.3  747.23   793.7  749.73   803.5   749.5   823.1  744.79
   832.9  743.14   842.7  742.87   862.3  743.76   891.7  748.75   911.3  747.69
#Mann= 3 , 0 , 0
       0     .06       0   137.7    .045       0   201.4     .06       0
Bank Sta=137.7,201.4
XS Rating Curve= 0 ,0
Exp/Cntr=0.3,0.1

Type RM Length L Ch R = 1 ,10330   ,403.7,411.3,418.8
XS GIS Cut Line= 2
     1829205.263      600830.683      1828332.88      600545.115
#Sta/Elev= 30
       0  818.95    19.5   815.2    39.1   809.8    58.6  803.41    87.9  792.64
   146.5  768.41     166  758.39   195.3   741.3   214.8  732.29   244.1  720.49
   302.7   698.7   312.5  696.61   351.6  693.28   419.9  685.71   436.2683.2944
   449.2  681.45     459  681.12   468.7  682.28   475.2684.1775   488.3  689.35
     498  694.52   527.3  711.37   654.3  779.86     664  784.18   673.8  787.67
   683.6  790.42   693.3  792.23   751.9  800.13   839.8  813.46   917.9  823.44
#Mann= 3 , 0 , 0
       0     .06       0   436.2    .045       0   475.2      .1       0
Bank Sta=436.2,475.2
XS Rating Curve= 0 ,0
Exp/Cntr=0.3,0.1

Type RM Length L Ch R = 1 ,9918.8  ,452.6,470.3,487.9
XS GIS Cut Line= 2
     1829347.166      600620.799     1828613.069      600062.824
#Sta/Elev= 30
       0  770.48   107.9  743.18   166.8  725.58     206  712.95   235.4  702.24
   245.2   699.1     255  696.88   284.5  694.22     363  690.72     412  685.39
   451.2  684.21   464.5682.8564   480.7  680.58   490.5  679.98   498.5680.9106
   510.1  684.78   549.3  711.07   559.1  716.98   568.9  721.58   627.8  746.47
   725.9  785.64   765.1  802.17   774.9  805.34   784.8  807.54   794.6  808.65
   863.2  809.19   882.8  811.53   892.6   814.5   902.5  819.06   922.1  829.96
#Mann= 3 , 0 , 0
       0     .06       0   464.5    .045       0   498.5      .1       0
Bank Sta=464.5,498.5
XS Rating Curve= 0 ,0
Exp/Cntr=0.3,0.1

Type RM Length L Ch R = 1 ,9448.5  ,480.9,483.1,485.2
XS GIS Cut Line= 2
      1829465.97      600662.299     1829336.378      599757.191
#Sta/Elev= 30
       0  747.94    19.7  747.19    39.3  744.99      59  743.56    68.8  742.29
   108.2  731.78   157.3  722.06   196.6  711.44   226.1  702.59     236   700.7
     295  695.65   393.3  688.69   442.2683.3967   462.1  680.29   471.9  680.38
   478.2682.4771   481.8  683.67   501.4  696.78   550.6  725.98   629.2  777.07
   658.7  795.35   678.4   806.8     698   816.5   786.5  856.26   845.5  887.04
   865.2     897   884.8   906.3   894.7  910.38   904.5  913.54   914.3  915.64
#Mann= 3 , 0 , 0
       0     .06       0   442.2    .045       0   478.2      .1       0
Bank Sta=442.2,478.2
XS Rating Curve= 0 ,0
Exp/Cntr=0.3,0.1

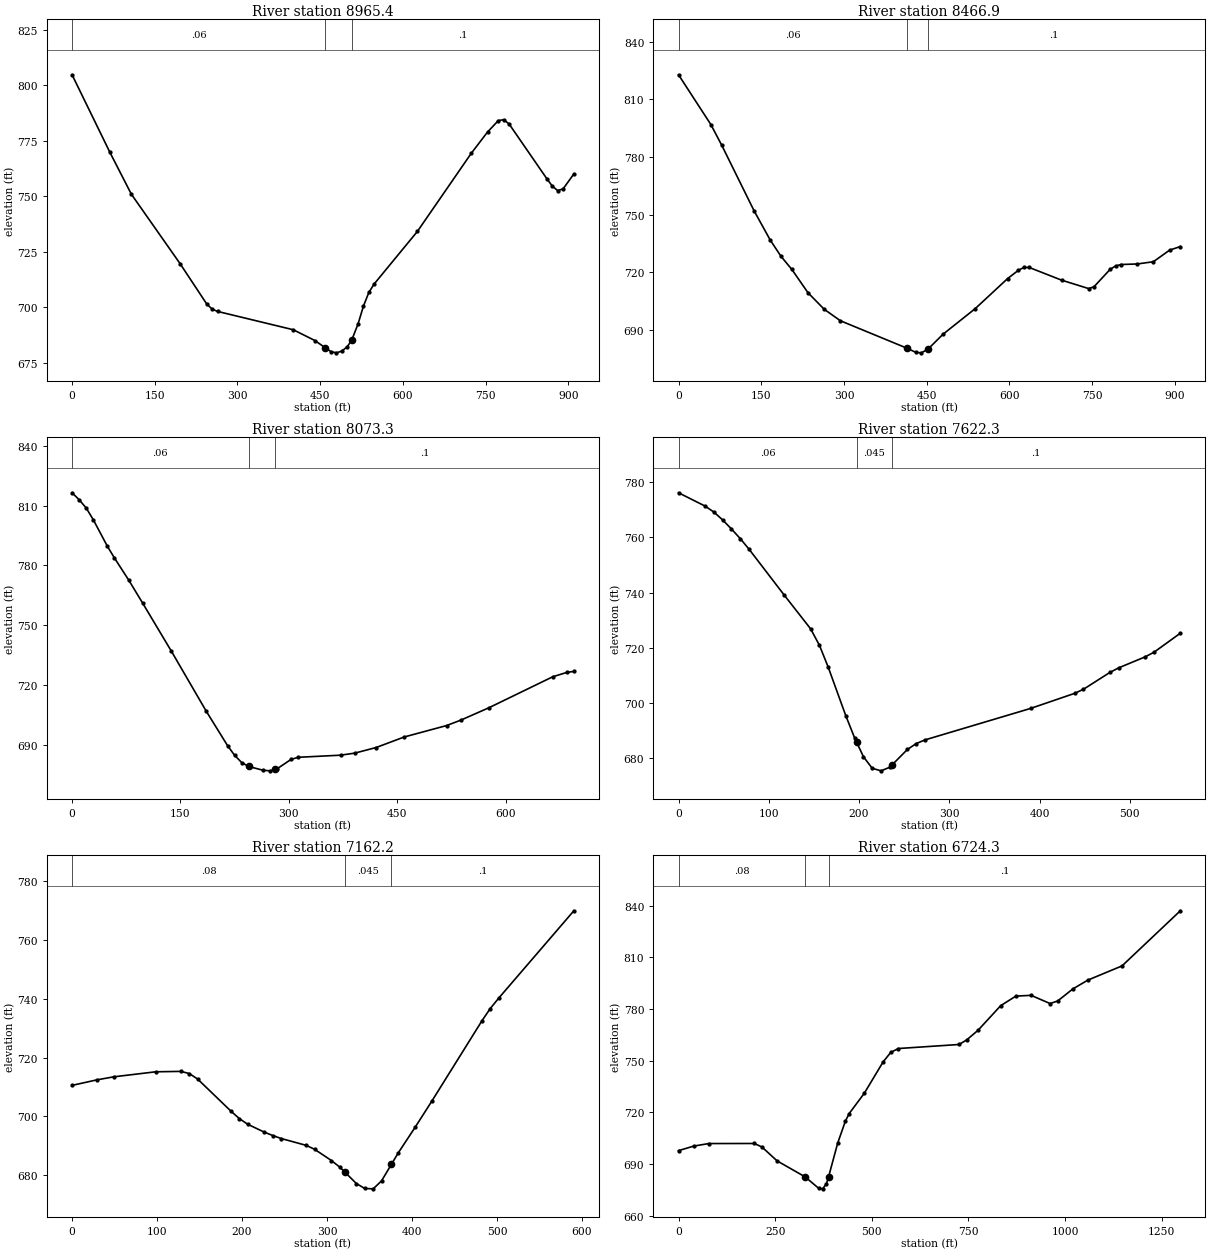
Type RM Length L Ch R = 1 ,8965.4  ,502.9,498.5,494.1
XS GIS Cut Line= 2
      1829905.38      600672.504     1829861.245      599763.575
#Sta/Elev= 30
       0  804.81    68.5  769.89   107.6  750.93   195.7  719.71   244.6  701.32
   254.4  699.09   264.2  698.09   401.2  689.85   440.3  684.99   459.3681.7163
   469.7  679.97   479.5  679.44   489.2  680.24     499  682.17   507.2 685.199
   518.6  692.44   528.4   700.5   538.2  706.67     548  710.54   626.2  734.17
   724.1  769.46   753.4  778.98     773  784.15   782.8  784.56   792.6  782.61
   861.1  757.91   870.9  754.62   880.6   752.6   890.4  753.35     910   760.1
#Mann= 3 , 0 , 0
       0     .06       0   459.3    .045       0   507.2      .1       0
Bank Sta=459.3,507.2
XS Rating Curve= 0 ,0
Exp/Cntr=0.3,0.1

Type RM Length L Ch R = 1 ,8466.9  ,400.9,393.6,386.3
XS GIS Cut Line= 2
     1830485.059      600606.044     1830267.628      599722.394
#Sta/Elev= 30
       0  822.81    58.7  796.86    78.3  786.14     137  751.97   166.4  736.68
   185.9  728.23   205.5  721.43   234.8  709.29   264.2  700.68   293.6   694.7
   414.5680.3835   430.5  678.22   440.3     678   452.2679.8707   479.5  687.65
   538.2  701.06   596.9  716.71   616.5  721.02   626.2  722.46     636  722.46
   694.7  715.85   743.7  711.47   753.4   712.4   782.8  721.51   792.6  723.24
   802.4     724   831.7  724.28   861.1  725.44   890.4  731.46     910  733.37
#Mann= 3 , 0 , 0
       0     .06       0   414.5    .045       0   452.2      .1       0
Bank Sta=414.5,452.2
XS Rating Curve= 0 ,0
Exp/Cntr=0.3,0.1

Type RM Length L Ch R = 1 ,8073.3  ,463.5,450.6,437.7
XS GIS Cut Line= 2
     1830907.533      600337.674     1830534.676      599751.595
#Sta/Elev= 30
       0  816.49     9.8     813    19.6  808.84    29.4  802.94    48.9  789.63
    58.7  783.74    78.3  772.72    97.8  761.05     137  737.25   185.9  706.74
   215.2  689.58     225   684.7   234.8  681.06   244.3679.1212   264.2  677.22
   273.9  676.91   281.3677.6711   283.7  677.92   303.3  682.68   313.1  683.71
   371.8  684.77   391.3   685.8   420.7  688.59   459.8  693.91   518.5  699.65
   538.1  702.36   577.2  708.61   665.3  724.12   684.8  726.31   694.6  726.83
#Mann= 3 , 0 , 0
       0     .06       0   244.3    .045       0   281.3      .1       0
Bank Sta=244.3,281.3
XS Rating Curve= 0 ,0
Exp/Cntr=0.3,0.1

Type RM Length L Ch R = 1 ,7622.3  ,457.8,460.4,463.1
XS GIS Cut Line= 2
     1831222.025      599853.068     1830716.845      599620.742
#Sta/Elev= 30
       0   776.2    29.3  771.39      39  769.24    48.8  766.38    58.5  763.11
    68.3   759.6      78  755.78   117.1  739.07   146.3  726.85   156.1  720.87
   165.8  712.96   185.4  695.23   195.1  687.23   197.4 685.627   204.9   680.4
   214.6  676.22   224.4  675.29   234.1  676.61   236.3677.3419   253.6  683.05
   263.4  685.19   273.1  686.52   390.2  697.95     439  703.42   448.7   704.9
     478  711.01   487.8  712.68     517  716.65   526.8  718.33     556  725.23
#Mann= 3 , 0 , 0
       0     .06       0   197.4    .045       0   236.3      .1       0
Bank Sta=197.4,236.3
XS Rating Curve= 0 ,0
Exp/Cntr=0.3,0.1

Type RM Length L Ch R = 1 ,7162.2  ,419.4,437.9,456.3
XS GIS Cut Line= 2
     1831429.122      599494.813     1830924.103      599188.885
#Sta/Elev= 30
       0  710.55    29.5  712.44    49.2  713.46    98.4  715.16   127.9   715.3
   137.8  714.58   147.6  712.73     187  701.78   196.8  699.27   206.7  697.34
   226.3  694.65   236.2  693.52     246  692.51   275.6  690.17   285.4  688.84
   305.1  685.04   314.9  682.81     321681.0909   334.6   677.2   344.4  675.54
   354.3  675.42   364.1  678.11   375.7683.7223   383.8  687.64   403.5  696.26
   423.2  705.16   482.2  732.45     492  736.63   501.9  740.14   590.4  769.83
#Mann= 3 , 0 , 0
       0     .08       0     321    .045       0   375.7      .1       0
Bank Sta=321,375.7
XS Rating Curve= 0 ,0
Exp/Cntr=0.3,0.1

Type RM Length L Ch R = 1 ,6724.3  ,634.9,675.5,716.1
XS GIS Cut Line= 3
     1831550.095       599420.84     1831285.551      598153.787
     1831284.796      598150.169
#Sta/Elev= 30
       0  697.82    39.2  700.46    78.4  701.94   196.1  701.98   215.7  699.95
     255  691.87   327.6 682.579   362.8   675.9   372.6  675.64   382.4  678.45
   388.3682.7365   411.8  702.25   431.5  714.86   441.3  719.32   480.5  731.13
   529.5  749.45   549.1  754.89   568.7  757.13   725.6  759.47   745.2  762.08
   774.7   767.7   833.5  782.03   872.7  787.57     912  788.01     961  783.26
   980.6   784.7  1019.8  791.69    1059  796.88  1147.3  805.11  1298.1  837.12
#Mann= 3 , 0 , 0
       0     .08       0   327.6    .045       0   388.3      .1       0
Bank Sta=327.6,388.3
XS Rating Curve= 0 ,0
Exp/Cntr=0.3,0.1

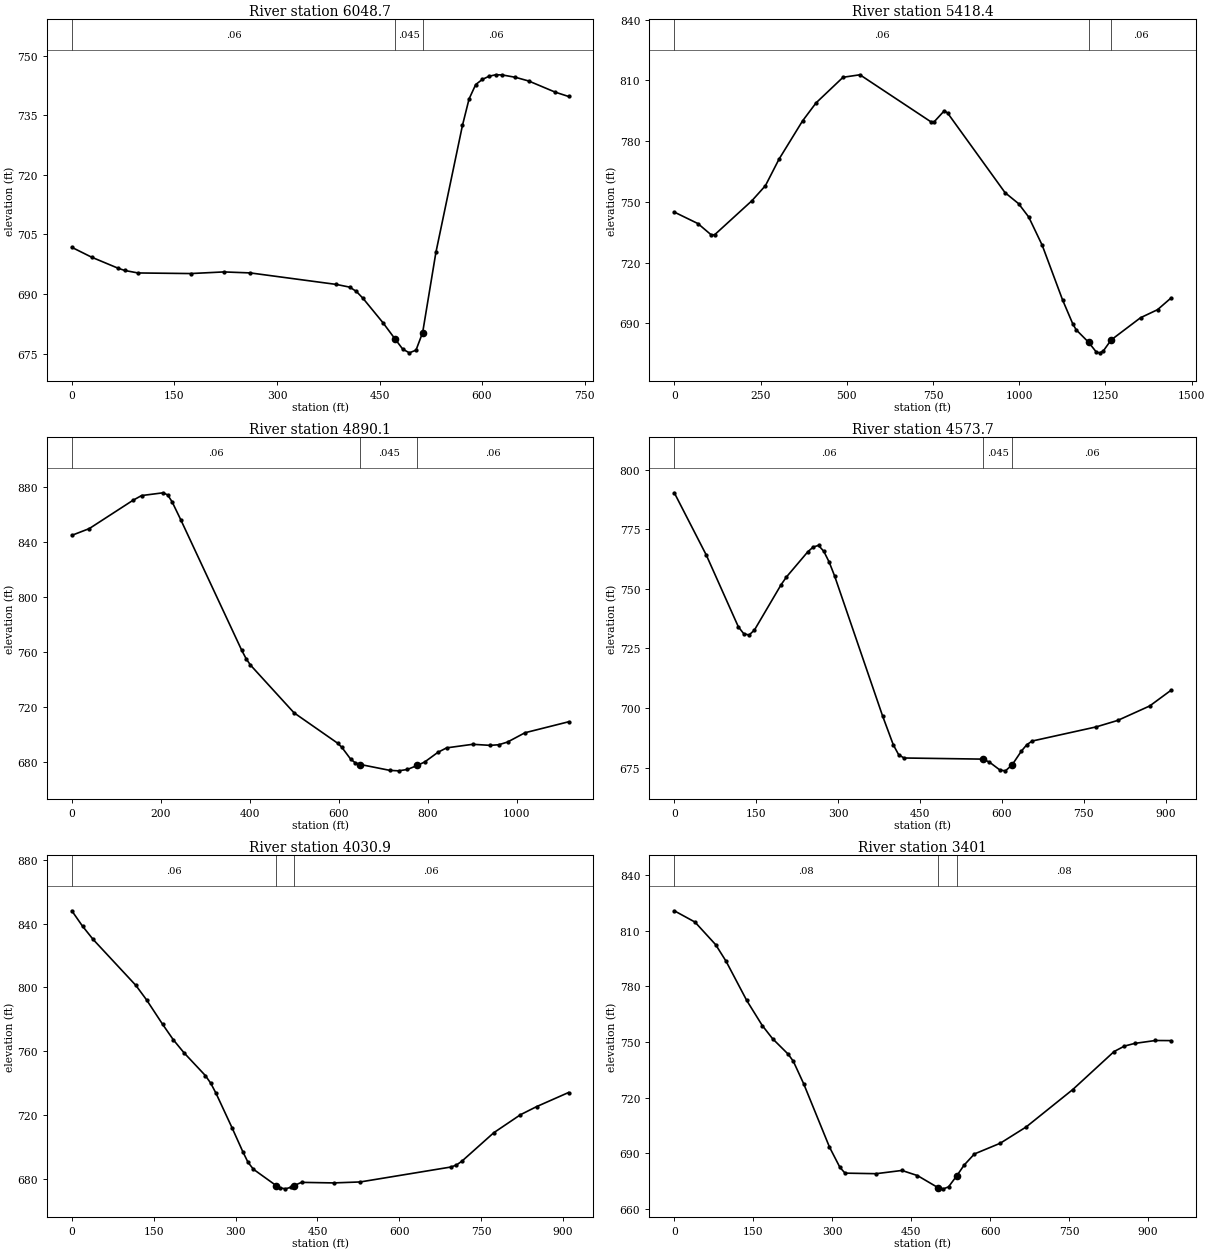
Type RM Length L Ch R = 1 ,6048.7  ,628.7,630.3,631.8
XS GIS Cut Line= 3
     1831505.314      599498.543     1831700.062      599283.648
     1832136.567      599283.648
#Sta/Elev= 30
       0  701.76      29  699.28    67.7   696.5    77.3  695.94    96.7  695.31
     174  695.16   222.3  695.57     261  695.32     387  692.42   406.4  691.74
   416.1  690.67   425.8  688.94   454.9  682.82   472.8678.6803     484  676.13
   493.7   675.2   503.4  675.88   513.1   680.3   532.5  700.49   571.3  732.44
     581  739.12   590.7  742.74   600.4  744.03   610.1  744.82   619.8   745.2
   629.5  745.16   648.9  744.56   668.3  743.63   707.1  740.82   726.5  739.74
#Mann= 3 , 0 , 0
       0     .06       0   472.8    .045       0   513.1     .06       0
Bank Sta=472.8,513.1
XS Rating Curve= 0 ,0
Exp/Cntr=0.3,0.1

Type RM Length L Ch R = 1 ,5418.4  ,565.7,528.3,490.8
XS GIS Cut Line= 3
     1830887.491       600687.18     1831356.239      599794.921
     1831787.363      599827.601
#Sta/Elev= 30
       0  744.92    68.5  739.24   107.6  733.58   117.4  733.78   225.1  750.54
   264.2  757.96   303.4     771   371.8  789.95     411  798.87   489.3  811.53
   538.2  812.76   743.7  789.56   753.5  789.54   782.8  794.97   792.6  793.82
     959  754.51   998.1   749.1  1027.6  742.48  1066.8  728.49  1125.8   701.5
  1155.3  689.71  1165.1  686.77  1201.1680.6074  1224.1  675.64  1233.9  675.37
  1243.7  676.26  1266.6681.7437  1351.8  692.72    1401  696.68  1440.2  702.47
#Mann= 3 , 0 , 0
       0     .06       0  1201.1    .045       0  1266.6     .06       0
Bank Sta=1201.1,1266.6
XS Rating Curve= 0 ,0
Exp/Cntr=0.3,0.1

Type RM Length L Ch R = 1 ,4890.1  ,335,316.4,297.8
XS GIS Cut Line= 2
     1831876.837      600911.688     1831860.044      599794.921
#Sta/Elev= 30
       0  845.04    39.2  849.94   137.2   870.5   156.8  874.01   205.7  876.04
   215.5  874.44   225.3  869.57   244.9  856.44   382.1  761.26   391.9  755.21
   401.7  750.55   499.7  715.76   597.6  693.67   607.4  690.53     627  682.02
   636.8   679.5     649678.1237   715.2  673.84   734.8  673.51   754.4  674.51
   777.2 677.478   793.6     680     823  686.96   842.6  690.23   901.4  692.84
   940.5  692.07   960.1  692.52   979.7  694.48  1018.9  701.25  1116.9  709.23
#Mann= 3 , 0 , 0
       0     .06       0     649    .045       0   777.2     .06       0
Bank Sta=649,777.2
XS Rating Curve= 0 ,0
Exp/Cntr=0.3,0.1

Type RM Length L Ch R = 1 ,4573.7  ,549.9,542.8,535.8
XS GIS Cut Line= 2
     1832572.083      600385.304      1831898.85      599773.049
#Sta/Elev= 30
       0  790.32    58.7  764.16   117.4  734.07   127.2  731.22     137  730.64
   146.8  732.73   195.7  751.77   205.5  755.01   244.6  765.57   254.4  767.54
   264.2  768.26     274  765.73   283.8  761.21   293.6  755.48   381.6   696.7
   401.2   684.6     411  680.45   420.8  679.07   565.4678.5943   577.3  677.34
   596.9  673.96   606.7  673.68     619676.2212     636     682   645.8  684.64
   655.6  686.18     773  692.12   812.2  694.82   870.9  700.89     910  707.48
#Mann= 3 , 0 , 0
       0     .06       0   565.4    .045       0     619     .06       0
Bank Sta=565.4,619
XS Rating Curve= 0 ,0
Exp/Cntr=0.3,0.1

Type RM Length L Ch R = 1 ,4030.9  ,637.5,629.7,621.9
XS GIS Cut Line= 2
     1832876.498      599787.008     1832048.067      599410.424
#Sta/Elev= 30
       0  848.06    19.6  838.43    39.1  830.08   117.4  801.27     137  792.19
   166.4  776.87   185.9  767.23   205.5  759.06   244.6  744.79   254.4  740.03
   264.2  733.65   293.6     712   313.1  697.17   322.9  690.33   332.7  686.04
   374.4   675.8   381.6  674.36   391.4  673.77   401.2  674.75   406.2675.6786
   420.8  677.83   479.5  677.48   528.4  678.09   694.7  687.46   704.5   688.7
   714.3  691.01     773  708.94   821.9  720.22   851.3  725.28     910  734.15
#Mann= 3 , 0 , 0
       0     .06       0   374.4    .045       0   406.2     .06       0
Bank Sta=374.4,406.2
XS Rating Curve= 0 ,0
Exp/Cntr=0.3,0.1

Type RM Length L Ch R = 1 ,3401    ,616.7,600.9,585.1
XS GIS Cut Line= 2
     1832983.895      599108.352     1832042.663      599042.471
#Sta/Elev= 30
       0  820.89    39.3  814.79    78.6  802.58    98.3  793.66   137.6  772.45
   167.1  758.93   186.7  751.81   216.2  743.49   226.1  739.62   245.7  727.51
   294.8  693.26   314.5  682.37   324.3  679.21   383.3  678.91   432.4  680.66
   461.9  677.89   500.8671.3945   511.1  670.73   520.9   671.8   536.7677.8416
   550.4  683.51     570  689.56   619.2  695.37   668.3  704.14   756.8  724.34
   835.4  744.89   855.1  747.83   874.7  749.28     914  750.84   943.5  750.78
#Mann= 3 , 0 , 0
       0     .08       0   500.8    .045       0   536.7     .08       0
Bank Sta=500.8,536.7
XS Rating Curve= 0 ,0
Exp/Cntr=0.3,0.1

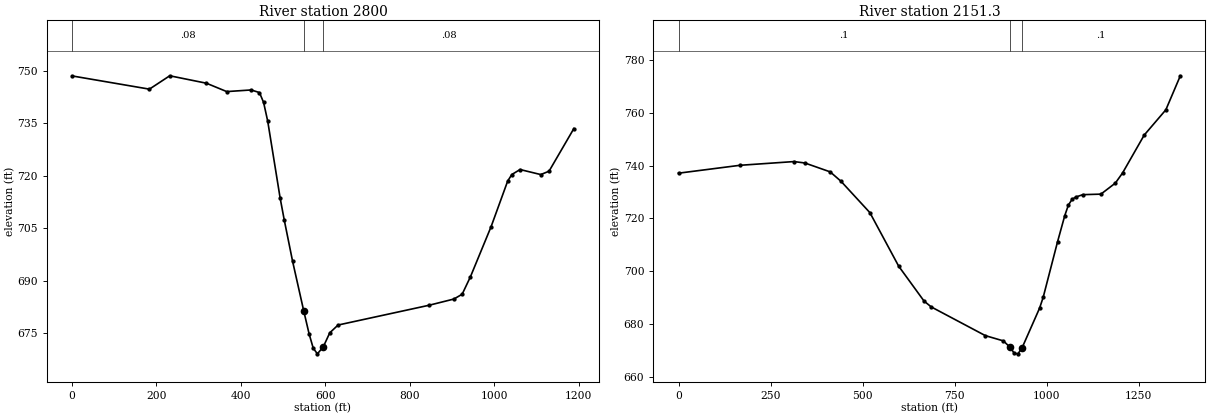
Type RM Length L Ch R = 1 ,2800    ,631.1,648.6,666
XS GIS Cut Line= 3
     1832943.224      598636.957     1832590.561      598401.061
     1831974.974      598854.223
#Sta/Elev= 30
       0  748.63   183.2  744.84   231.4  748.67   318.2  746.54   366.4  744.14
   424.3  744.61   443.9  743.86   453.7  741.04   463.5  735.65   492.9  713.64
   502.7  707.32   522.3  695.58   548.7681.3606   561.5  674.74   571.3  670.63
   581.1  669.01     595670.9868   610.5  675.04   630.1  677.26   845.7  682.93
   904.5  684.71   924.1  686.09   943.7  691.09   992.7  705.46  1031.9   718.5
  1041.7  720.38  1061.3  721.81  1110.3  720.37  1129.9  721.33  1188.7  733.55
#Mann= 3 , 0 , 0
       0     .08       0   548.7    .045       0     595     .08       0
Bank Sta=548.7,595
XS Rating Curve= 0 ,0
Exp/Cntr=0.3,0.1

Type RM Length L Ch R = 1 ,2151.3  ,651.5,671,690.7
XS GIS Cut Line= 2
       1832824.3      598336.502     1831473.889      598152.629
#Sta/Elev= 30
       0  737.11   166.7  740.09   313.8   741.5   343.2  740.96   411.8  737.61
   441.2  734.06   519.7   722.2   598.1  701.92   666.7  688.79   686.3  686.56
   833.4   675.7   882.4  673.71   900.2671.3281   911.8  669.05   921.6  668.82
   932.3670.8461   980.5  686.05   990.3  690.12  1029.5  711.22  1049.1   721.1
  1058.9  725.07  1068.7  727.17  1078.5  728.07  1098.1  728.99  1147.2  729.19
  1186.4  733.36    1206  737.19  1264.8  751.51  1323.6  761.07  1362.9  773.93
#Mann= 3 , 0 , 0
       0      .1       0   900.2    .045       0   932.3      .1       0
Bank Sta=900.2,932.3
XS Rating Curve= 0 ,0
Exp/Cntr=0.3,0.1