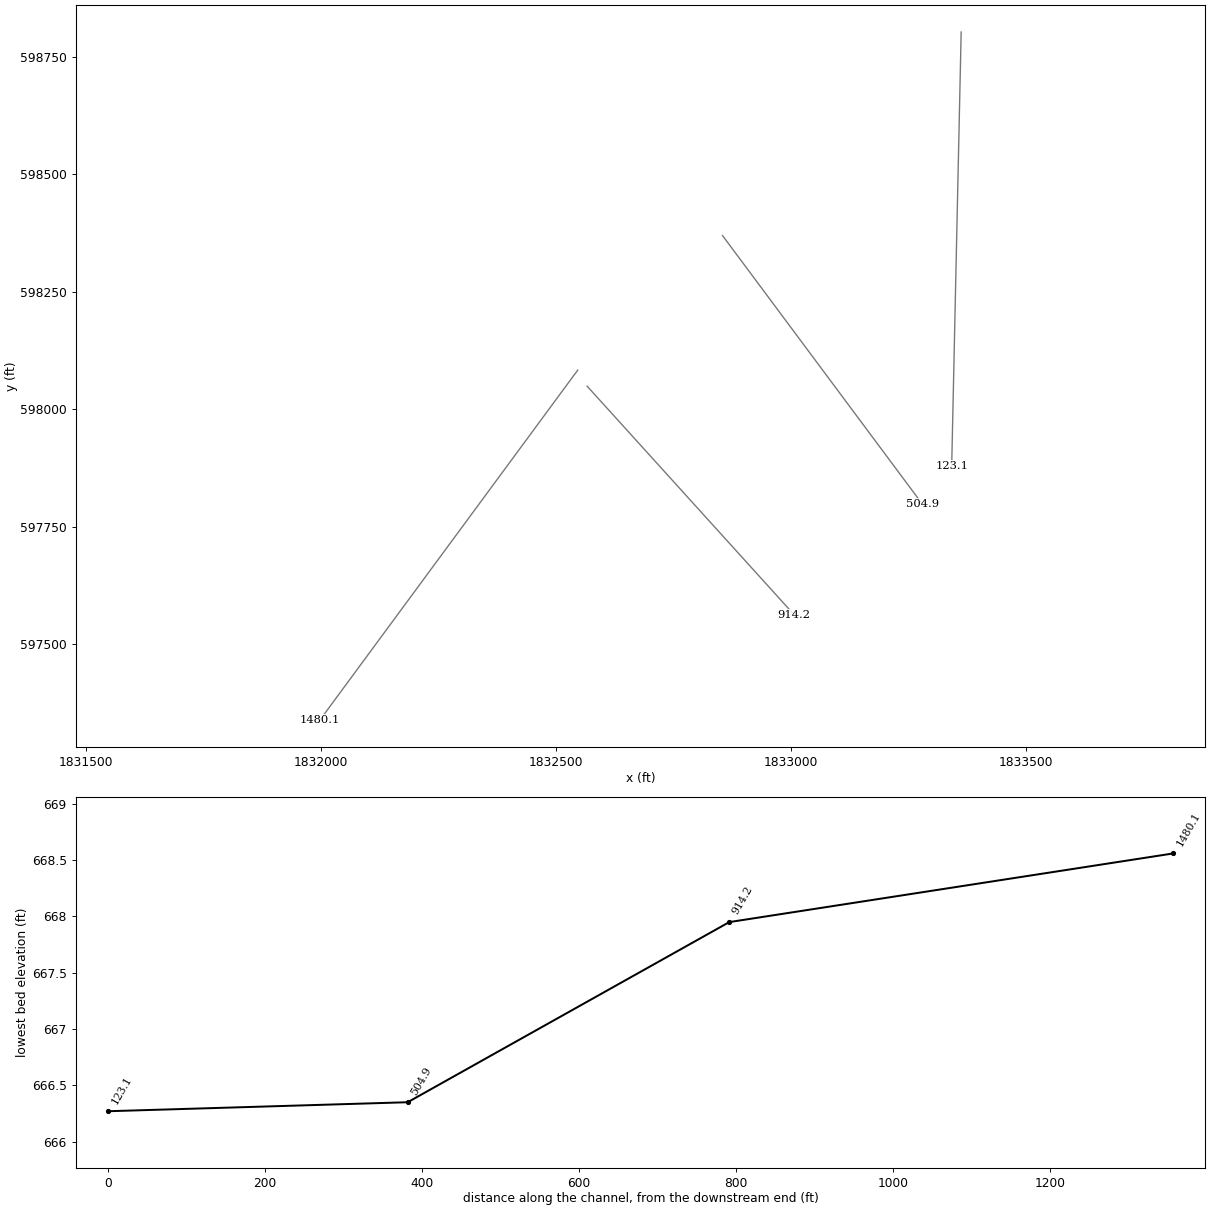
HEC-RAS study FlatFork.prj: FlatFork

--- FlatFork.g01 (geometry) --- (continued)

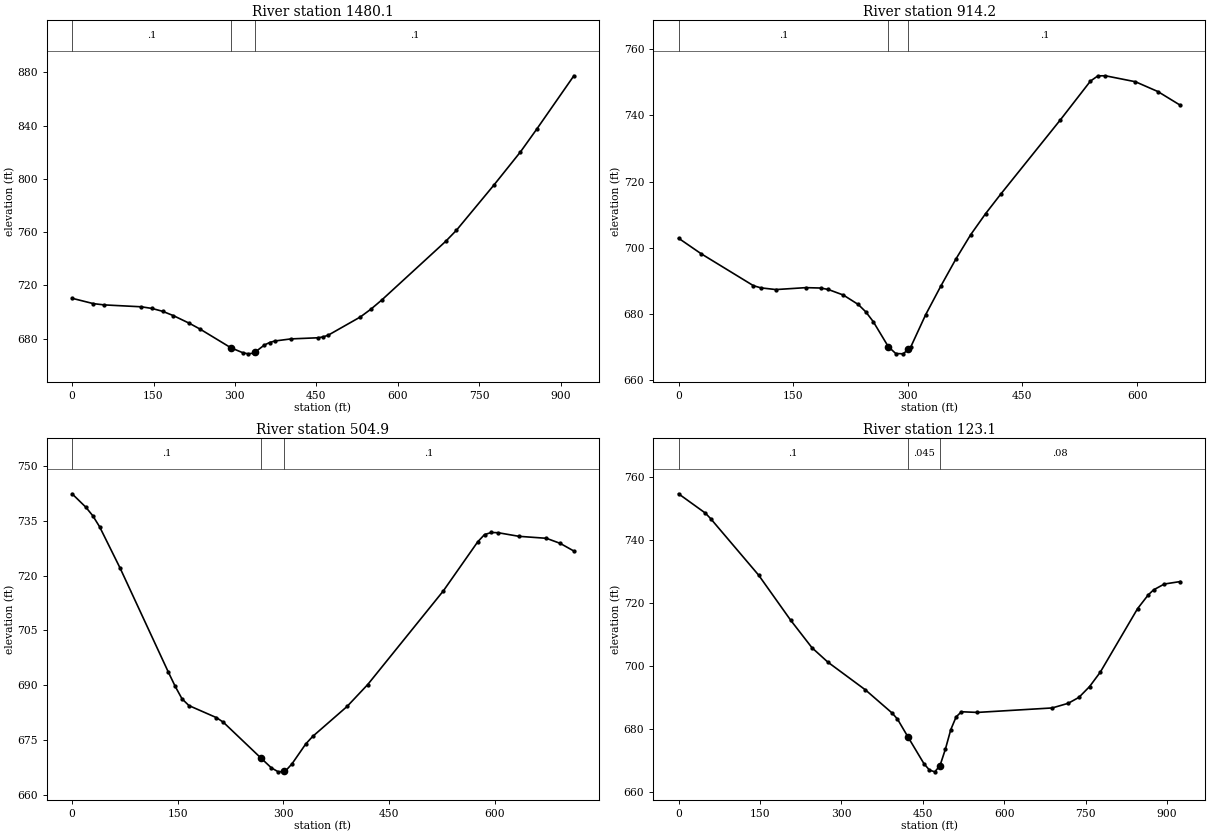
Type RM Length L Ch R = 1 ,1480.1  ,535,565.6,596.3
XS GIS Cut Line= 2
     1832546.663      598083.281     1831998.406       597339.15
#Sta/Elev= 30
       0  710.31    39.3  706.28      59  705.34   127.8   703.9   147.5  702.65
   167.2  700.46   186.8  697.23   216.3  691.47     236   687.1   292.6673.1019
   314.6  669.38   324.5  668.56   334.3  669.09   337.7670.0104     354  675.12
   363.8  677.06   373.6  678.22   403.2  679.78   452.3  680.62   462.2  681.26
     472  682.62     531  696.27   550.6  702.17   570.3  708.96   688.3  753.13
     708  761.42   776.8  795.27     826  820.34   855.5  837.17   924.3   877.5
#Mann= 3 , 0 , 0
       0      .1       0   292.6    .045       0   337.7      .1       0
Bank Sta=292.6,337.7
XS Rating Curve= 0 ,0
Exp/Cntr=0.3,0.1

Type RM Length L Ch R = 1 ,914.2   ,411.7,409.5,407.4
XS GIS Cut Line= 2
     1832566.873      598049.039     1833007.612      597562.383
#Sta/Elev= 30
       0  702.89    29.4  698.22      98  688.54   107.8  687.88   127.4  687.37
   166.6  687.95   186.2  687.83     196  687.39   215.6  685.72   235.2  682.86
     245  680.64   254.8  677.68   274.5670.1187   284.2  668.05     294  667.95
   300.8669.3679   303.8  669.99   323.4  679.79     343  688.33   362.6  696.47
   382.2  703.92   401.8  710.31   421.4  716.14   499.8  738.69     539  750.36
   548.8  751.94   558.6  751.96   597.8  750.16   627.2   747.2   656.6  743.05
#Mann= 3 , 0 , 0
       0      .1       0   274.5    .045       0   300.8      .1       0
Bank Sta=274.5,300.8
XS Rating Curve= 0 ,0
Exp/Cntr=0.3,0.1

Type RM Length L Ch R = 1 ,504.9   ,396.8,381.8,366.8
XS GIS Cut Line= 2
      1832855.02       598369.73     1833280.221      597798.323
#Sta/Elev= 30
       0  742.37    19.5  738.71    29.3  736.39      39  733.38    68.3     722
   136.6  693.63   146.4  689.71   156.1   686.3   165.9  684.46   204.9  681.17
   214.6  679.93   267.9670.1534   282.8  667.45   292.7  666.35   300.8666.4747
   302.5   666.5   312.2  668.55   331.7  673.98   341.5  676.03   390.3  684.22
   419.6  690.21   526.9  715.81   575.7  729.22   585.4  731.22   595.2  731.79
   604.9  731.72   634.2  730.74   673.2   730.2   692.7  728.82   712.2  726.72
#Mann= 3 , 0 , 0
       0      .1       0   267.9    .045       0   300.8      .1       0
Bank Sta=267.9,300.8
XS Rating Curve= 0 ,0
Exp/Cntr=0.3,0.1

Type RM Length L Ch R = 1 ,123.1   ,125.5,123.1,120.7
XS GIS Cut Line= 2
     1833362.998      598803.178     1833342.819      597879.106
#Sta/Elev= 30
       0  754.66    49.2  748.55      59  746.79   147.5  728.81   206.5  714.48
   245.8  705.72   275.3  701.11   344.2  692.33   393.3  684.98   403.2  683.06
   422.8  677.31   452.3   668.8   462.2  666.84     472  666.27   481.6 668.239
   491.6  673.51   501.5   679.7   511.3  683.73   521.1  685.37   550.6  685.16
   688.3  686.58   717.8  688.06   737.5  689.94   757.1  693.37   776.8  697.94
   845.6  718.16   865.3  722.54   875.1  724.12   894.8  725.97   924.3  726.76
#Mann= 3 , 0 , 0
       0      .1       0   422.8    .045       0   481.6     .08       0
Bank Sta=422.8,481.6
XS Rating Curve= 0 ,0
Exp/Cntr=0.3,0.1

Chan Stop Cuts=-1
Use User Specified Reach Order=0
Composite Channel Slope=5